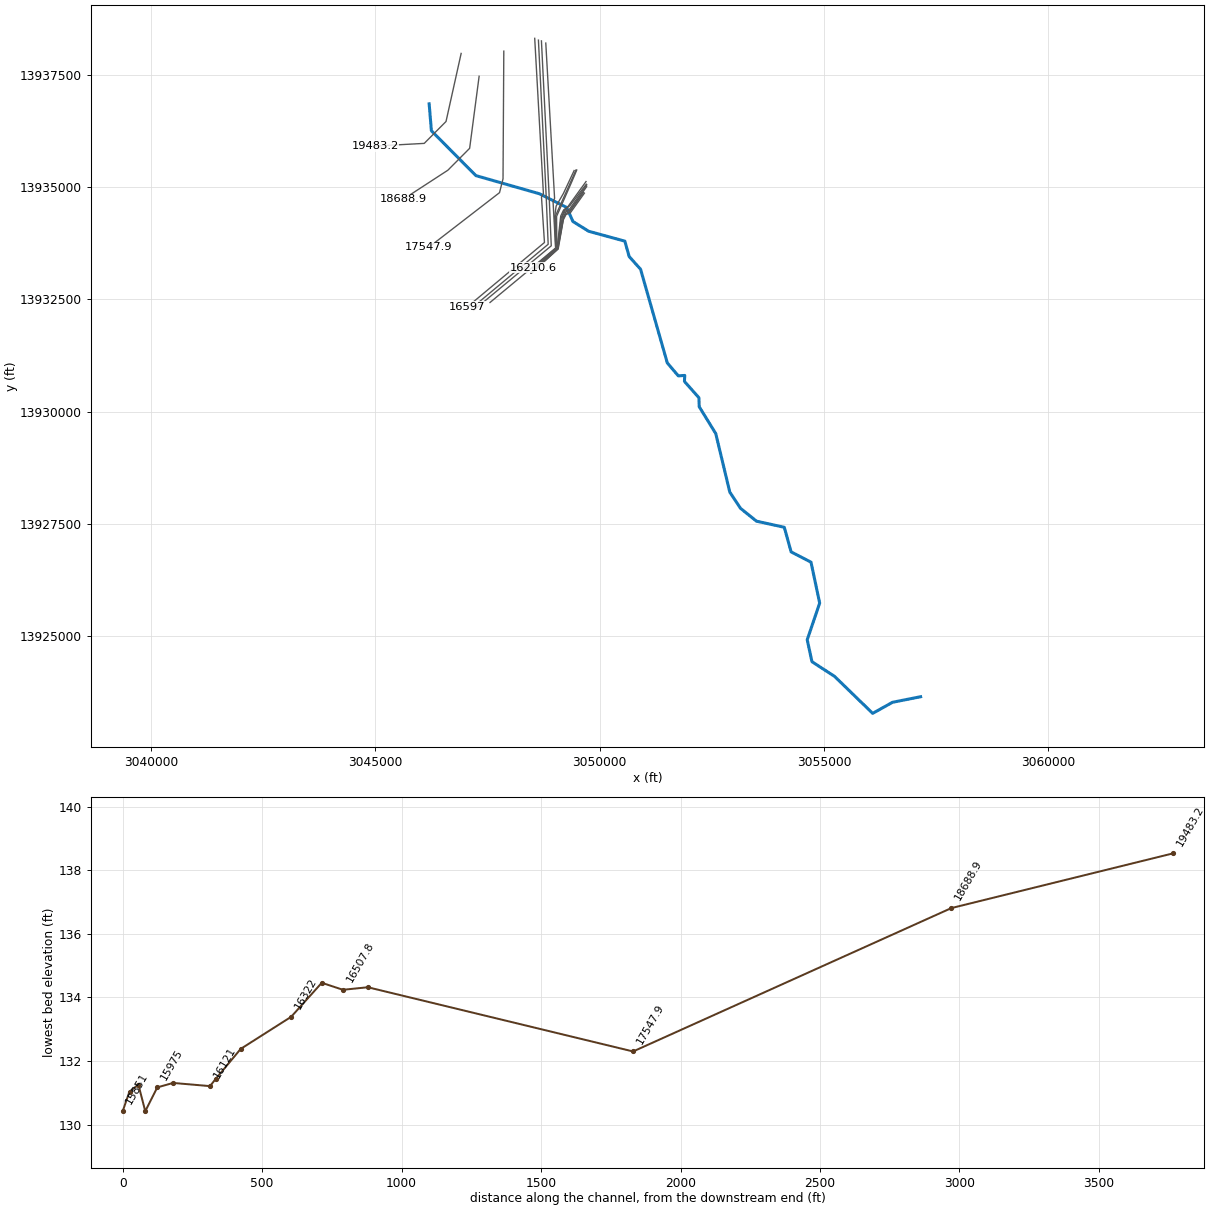
--- K140-00-00.prj (project) ---

Proj Title=K140-00-00
Current Plan=p02
Default Exp/Contr=.3,.1
English Units
Geom File=g01
Flow File=f01
Flow File=f02
Plan File=p01
Plan File=p02
Y Axis Title=Elevation
X Axis Title(PF)=Main Channel Distance
X Axis Title(XS)=Station
BEGIN DESCRIPTION:
HCFCD MODEL SUMMARY METADATA
The purpose of this summary is to document the high points of hydrologic and hydraulic models filed within the HCFCD Model and Map Management (M3) system.  The document includes references to the project that prompted the creation or update of the model.
DESCRIPTION OF PROJECT:
The following model was the hydraulic model which represented the effective condition of Harris County's watersheds.
PURPOSE OF PROJECT:
Development of effective models to support the National Flood Insurance Program.
HCFCD Watershed Unit ID: K
M3 Study Identifier: 2007_Effective_K
Engineer: HCFCD
Project Name: EffectiveFEMA Study for watershed Cypress Creek (K)
Study Completion Date: 6/18/2007
FEMA Case Number: [No Data]
FEMA Approval Date: [No Date in Database]
Vertical Datum: NAVD 1988
Datum Note: 2001 ADJ
HYDRAULICS
HCFCD Unit No.:  K140-00-00
Hydraulic Program Name: HEC-RAS
Hydraulic Program Version: 3.0.1
Steady Hydraulic Model: Yes
Unsteady Hydraulic Model: No
Update1:
The effective FEMA hydraulic model for unit number K140-00-00 has been updated by FEMA LOMR 17-06-1728P with an effective date of 6/11/2018.
END DESCRIPTION:
DSS Export Rating Curves= 0
DSS Export Rating Curve Sorted= 0
DSS Export Volume Flow Curves= 0
DXF OffsetX= 0
DXF OffsetY= 0
DXF ScaleX= 1
DXF ScaleY= 10

--- K140-00-00.p02 (plan) ---

Plan Title=Effective Floodway 2018
Version=Version 3.0.1  May 2012
Short Identifier=Eff+ LOMR FW
Geom File=g01
Flow File=f02
Subcritical Flow
K Sum by GR= 0
Std Step Tol= 0.01
Critical Tol= 0.01
Num of Std Step Trials= 20
Max Error Tol= 0.3
Flow Tol Ratio= 0.001
Split Flow NTrial= 30
Split Flow Tol= 0.02
Split Flow Ratio= 0.02
Log Output Level= 0
Friction Slope Method= 1
Unsteady Friction Slope Method= 2
Parabolic Critical Depth
Global Vel Dist= 0 , 0 , 0
Global Log Level= 0
CheckData=True
Encroach Param=-1 ,0,0, 2
Encroach River=K140-00-00
Encroach Reach=K140-00-00_00011
Encroach Node=19483.2
       1 4790.37 5245.84
Encroach Node=18688.9
       1 4761.72 5291.29
Encroach Node=17547.9
       1 4735.76 5242.74
Encroach Node=16597
       1  4919.1  5066.6
Encroach Node=16507.8
       1  4919.1  5066.6
Encroach Node=16469.8
       1  4919.1  5066.6
Encroach Node=16431.8
       1  4919.1  5066.6
Encroach Node=16322
       1  4941.5  5066.6
Encroach Node=16210.6
       1 4965.96 5045.59
Encroach Node=16141
       1 4950.22 5045.35
Encroach Node=16121
       1 4948.68 5046.91
Encroach Node=15989
       1    4967    5047
Encroach Node=15975
       1 4964.58 5039.63
Encroach Node=15932
       1    4956    5041
Encroach Node=15907.5
       1    4956    5041
Encroach Node=15891.5
       1    4956    5041
Encroach Node=15875.5
       1    4956    5041
Encroach Node=15851
       1    4956    5041
Encroach Node=15735.5
       1 4960.66 5040.92
Encroach Node=15669.8
       1 4948.08 5035.36
Encroach Node=15589.5
       1  4943.4  5083.4
Encroach Node=15483
       1 4955.34 5045.93
Encroach Node=15394
       1 4955.35 5046.33
Encroach Node=15301
       1 4956.16    5037
Encroach Node=15216
       1    4956 5042.73
Encroach Node=15130
       1 4959.12 5043.55
Encroach Node=15012
       1 4959.65 5046.62
Encroach Node=14905
       1 4959.78 5044.79
Encroach Node=14804
       1 4955.15  5042.4
Encroach Node=14640
       1  4954.8  5054.1
Encroach Node=13828
       1 4880.27 5128.64
Encroach Node=12902
       1 4886.28 5109.12
Encroach Node=12802
       1 4886.28 5109.12
Encroach Node=12769.5
       1 4886.28 5109.12
Encroach Node=12737
       1 4886.28 5109.12
Encroach Node=12637
       1 4886.28 5109.12
Encroach Node=11476
       1 4883.89 5109.81
Encroach Node=11376.3
       1 4883.89 5109.81
Encroach Node=11350.8
       1 4883.89 5109.81
Encroach Node=11325.3
       1 4883.89 5109.81
Encroach Node=11225
       1 4883.89 5109.81
Encroach Node=10982.9
       1 4904.13 5092.67
Encroach Node=10131.2
       1    4978  5055.8
Encroach Node=9664.4
       1  4914.4  5054.7
Encroach Node=8998.4
       1    4952    5082
Encroach Node=8171
       1  4938.3  5078.3
Encroach Node=8071.3
       1 4914.46 5092.04
Encroach Node=8043.8
       1 4914.46 5092.04
Encroach Node=8016.3
       1 4914.46 5092.04
Encroach Node=7916
       1  4932.2  5078.6
Encroach Node=7281.9
       1  4934.8    5065
Encroach Node=7162
       1    4937 5062.98
Encroach Node=7062.8
       1 4930.34 5067.67
Encroach Node=7052.3
       1 4930.34 5067.67
Encroach Node=7041.8
       1 4930.34 5067.67
Encroach Node=6941
       1  4937.9  5072.2
Encroach Node=5903.5
       1  4936.4  5062.5
Encroach Node=4927
       1  4937.5  5113.5
Encroach Node=4827.8
       1 4914.79 5113.91
Encroach Node=4762.15
       1 4914.79 5113.91
Encroach Node=4696.5
       1 4914.79 5113.91
Encroach Node=4596
       1 4914.79 5113.91
Encroach Node=3740.9
       1 4908.86 5108.69
Encroach Node=3301.7
       1 4839.34 5138.27
Encroach Node=2997
       1 4877.71 5111.79
Encroach Node=2897.7
       1 4877.71 5111.79
Encroach Node=2870.7
       1 4877.71 5111.79
Encroach Node=2843.7
       1 4877.71 5111.79
Encroach Node=2793.6
       1 4892.45 5112.36
Encroach Node=2765.1
       1 4892.45 5112.36
Encroach Node=2736.6
       1 4892.45 5112.36
Encroach Node=2636
       1 4892.45 5112.36
Encroach Node=2356.9
       1 4912.01  5095.7
Encroach Node=1109.7
       1 4793.31 5148.89
Encroach Node=1068.6
       1 4822.09 5172.52
BEGIN DESCRIPTION:
FEMA Effective Floodway May 2018 + LOMR 17-06-1728P
END DESCRIPTION:
Computation Interval=1HOUR
Output Interval=1HOUR
Run HTab= 0
Run UNet= 0
Run PostProcess= 0
UNET Theta= 1
UNET ZTol= 0.02
UNET ZSATol= 0.1
UNET MxIter= 20
UNET MaxInSteps= 20
UNET DtIC= 0
UNET DtMin= 0
UNET MaxCRTS= 20
UNET WFStab= 2
UNET SFStab= 1
UNET WFX= 1
UNET SFX= 1
UNET Convert EG Bridges=-1
UNET Use Existing IB Tables=-1
Instantaneous Interval=1HOUR
Write IC File= 0
Write Velocity= 0
Write Detailed= 0

--- K140-00-00.p01 (plan) ---

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Plan Title=Effective Multi-profile 2018
Short Identifier=Eff+ LOMR MP
Geom File=g01
Flow File=f01
FEMA Effective Multi-Profile May 2018 + LOMR 17-06-1728P

--- K140-00-00.f02 (steady flow) ---

Flow Title=Effective Floodway 2018
Version=Version 3.0.1  May 2012
Number of Profiles= 2
Profile Names=1PCT_100yr, 1PCTFloodway_100yrFW
River Rch & RM=K140-00-00,K140-00-00_00011,19483.2
    1019    1019
River Rch & RM=K140-00-00,K140-00-00_00011,17547.9
    1139    1139
River Rch & RM=K140-00-00,K140-00-00_00011,16431.8
    1243    1243
River Rch & RM=K140-00-00,K140-00-00_00011,15875.5
    1483    1483
River Rch & RM=K140-00-00,K140-00-00_00011,14640.0
    1870    1870
River Rch & RM=K140-00-00,K140-00-00_00011,12802.0
    2030    2030
River Rch & RM=K140-00-00,K140-00-00_00011,11376.3
    2190    2190
River Rch & RM=K140-00-00,K140-00-00_00011,10131.2
    2250    2250
River Rch & RM=K140-00-00,K140-00-00_00011,9664.4
    2360    2360
River Rch & RM=K140-00-00,K140-00-00_00011,8071.3
    2430    2430
River Rch & RM=K140-00-00,K140-00-00_00011,7062.8
    2520    2520
River Rch & RM=K140-00-00,K140-00-00_00011,5903.5
    2600    2600
River Rch & RM=K140-00-00,K140-00-00_00011,4827.8
    2698    2698
Boundary for River Rch & Prof#=K140-00-00,K140-00-00_00011, 1
Up Type= 0
Dn Type= 1
Dn Known WS=113.99
Boundary for River Rch & Prof#=K140-00-00,K140-00-00_00011, 2
Up Type= 0
Dn Type= 1
Dn Known WS=114.99
DSS Import GetInterval= 0
DSS Import GetPeak= 0
DSS Import FillOption= 0

--- K140-00-00.f01 (steady flow) ---

Flow Title=Effective Multi-Profile 2018
Version=Version 3.0.1  May 2012
Number of Profiles= 4
Profile Names=10PCT_10yr, 2PCT_50yr, 1PCT_100yr, 0.2PCT_500yr
River Rch & RM=K140-00-00,K140-00-00_00011,19483.2
     579     878    1019    1452
River Rch & RM=K140-00-00,K140-00-00_00011,17547.9
     642     979    1139    1629
River Rch & RM=K140-00-00,K140-00-00_00011,16431.8
     696    1065    1243    1783
River Rch & RM=K140-00-00,K140-00-00_00011,15875.5
     820    1265    1483    2141
River Rch & RM=K140-00-00,K140-00-00_00011,14640
     960    1600    1870    2740
River Rch & RM=K140-00-00,K140-00-00_00011,12802
    1060    1730    2030    2980
River Rch & RM=K140-00-00,K140-00-00_00011,11376.3
    1160    1850    2190    3210
River Rch & RM=K140-00-00,K140-00-00_00011,10131.2
    1200    1900    2250    3300
River Rch & RM=K140-00-00,K140-00-00_00011,9664.4
    1260    1980    2360    3460
River Rch & RM=K140-00-00,K140-00-00_00011,8071.3
    1300    2030    2430    3560
River Rch & RM=K140-00-00,K140-00-00_00011,7062.8
    1350    2090    2520    3680
River Rch & RM=K140-00-00,K140-00-00_00011,5903.5
    1400    2150    2600    3800
River Rch & RM=K140-00-00,K140-00-00_00011,4827.8
    1388    2247    2698    4012
Boundary for River Rch & Prof#=K140-00-00,K140-00-00_00011, 1
Up Type= 0
Dn Type= 3
Dn Slope=3.471777E-03
Boundary for River Rch & Prof#=K140-00-00,K140-00-00_00011, 2
Up Type= 0
Dn Type= 3
Dn Slope=3.471777E-03
Boundary for River Rch & Prof#=K140-00-00,K140-00-00_00011, 3
Up Type= 0
Dn Type= 3
Dn Slope=3.471777E-03
Boundary for River Rch & Prof#=K140-00-00,K140-00-00_00011, 4
Up Type= 0
Dn Type= 3
Dn Slope=3.471777E-03
DSS Import GetInterval= 0
DSS Import GetPeak= 0
DSS Import FillOption= 0

--- K140-00-00.g01 (geometry) ---

Geom Title=K140-00-00 2018
Version=Version 3.0.1  May 2012

River Reach=K140-00-00      ,K140-00-00_00011
Reach XY= 30
      3046199.28     13936851.97      3046249.13     13936252.34
      3047241.15     13935253.91      3048656.89     13934850.13
      3049265.06     13934544.62      3049404.64     13934231.99
      3049755.02     13934014.78      3050561.75       13933794.
       3050657.3      13933452.9      3050912.06     13933169.01
      3051508.17     13931082.46      3051752.97     13930794.27
      3051897.06     13930803.82      3051890.55     13930670.57
      3052213.76     13930306.31      3052219.75       13930107.
      3052588.25       13929509.        3052901.       13928206.
      3053139.25       13927845.       3053496.4     13927558.06
      3054116.19     13927421.77       3054268.5       13926874.
      3054711.75       13926645.      3054905.26      13925733.4
      3054627.29     13924916.56      3054733.01     13924428.54
      3055237.34     13924101.01      3056087.01     13923277.35
      3056526.78     13923523.33      3057155.26      13923648.3

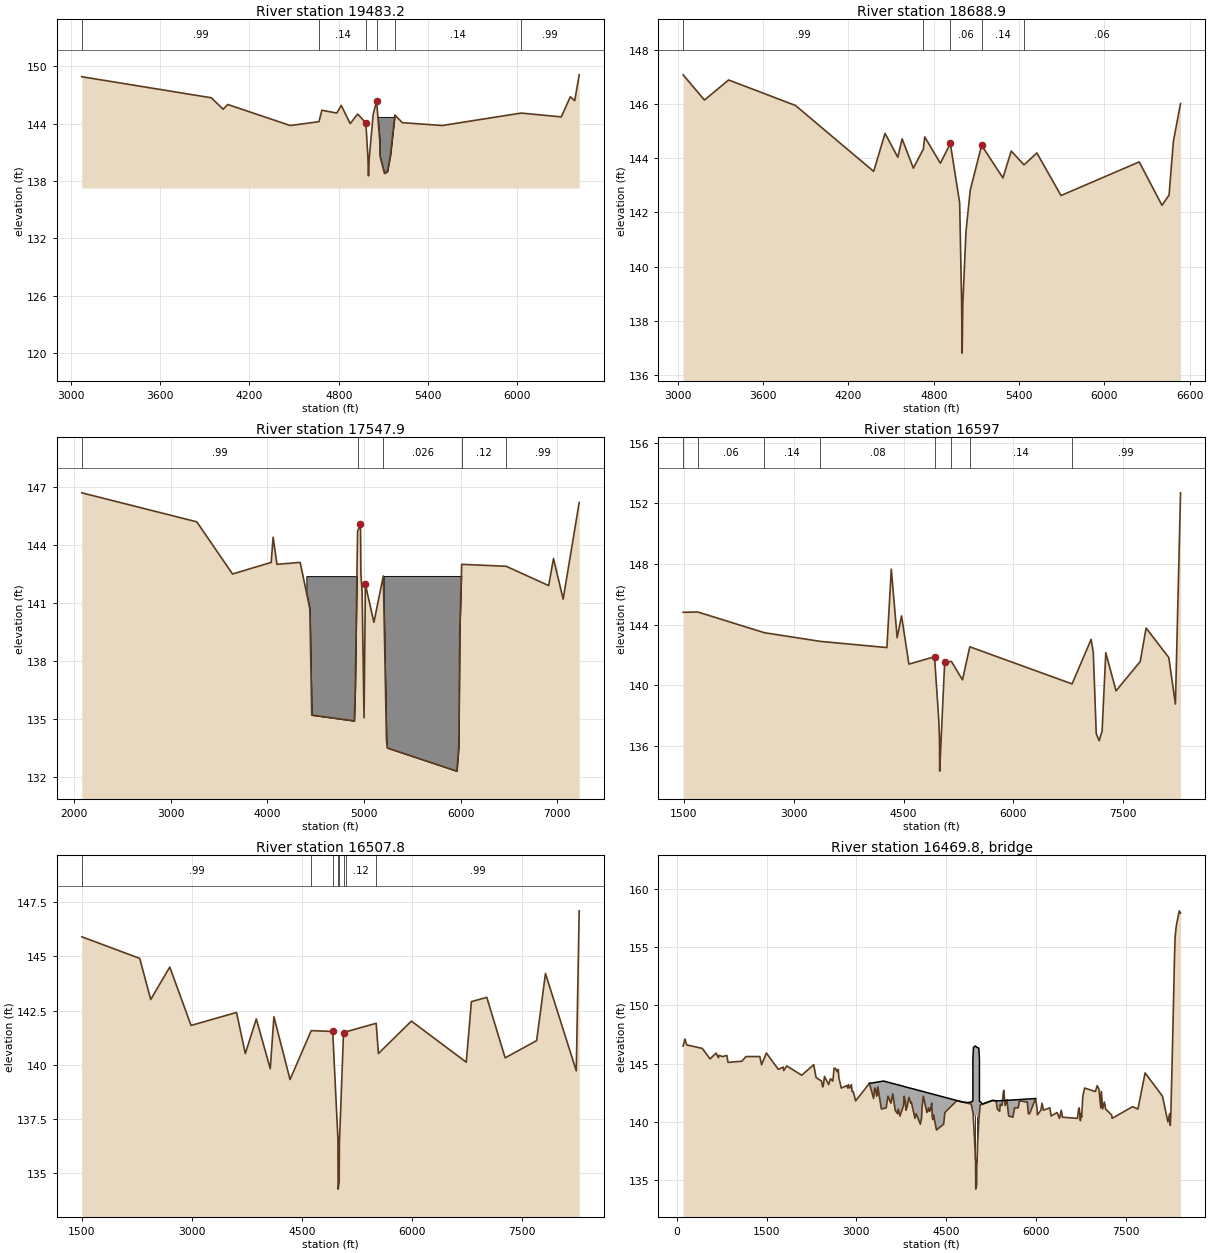
Type RM Length L Ch R = 1 ,19483.2 ,794.3,794.3,794.3
BEGIN DESCRIPTION:
Cross Section K140-00-00-X06; Detention pond on right 11/13/2 VRR; Roadway and drainage ditch for it on far right blocked out by levee VRR
END DESCRIPTION:
XS GIS Cut Line= 4
 3046912.284685113937975.2886999      3046575.16     13936459.33
      3046089.41     13935971.61 3044991.090919313935912.1100288
#Sta/Elev= 30
  3073.7   148.9  3943.7   146.7  4023.7   145.5  4053.7     146  4473.7   143.8
  4666.7   144.2  4686.7   145.4  4786.7   145.1  4816.7   145.9  4876.7     144
  4926.7     145  4982.1  144.07  4995.6  140.49  4999.5  138.53  5004.4  140.35
  5031.1  144.97  5054.1  146.35  5075.4  142.18  5076.7   140.6  5106.7   138.8
  5126.7     139  5146.7   140.7  5176.7   144.9  5226.7   144.1    5495   143.8
    6025   145.1    6295   144.7    6355   146.8    6385   146.4    6415   149.1
#Mann= 6 ,-1 , 0
  3073.7     .99       0  4666.7     .14       0  4982.1     .06       0
  5054.1    .026       0  5176.7     .14       0    6025     .99       0
#Block Obstruct= 2 ,-1
 5053.87 5176.74   144.7    5177    5178     120
Bank Sta=4982.1,5054.1
XS Rating Curve= 0
Exp/Cntr=.3,.1

Type RM Length L Ch R = 1 ,18688.9 ,875,1141,1141
BEGIN DESCRIPTION:
Interpolated XS
END DESCRIPTION:
XS GIS Cut Line= 4
 3047313.122295313937466.8575256      3047101.57     13935861.53
      3046615.82     13935373.82      3045617.57     13934724.83
#Sta/Elev= 30
  3037.3  147.07  3187.3  146.14  3357.3  146.88  3827.3  145.94  4377.3  143.51
  4457.3  144.91  4547.3  144.03  4577.3  144.71  4656.5  143.63  4726.5  144.33
  4736.5  144.78  4846.5  143.81  4916.5  144.54  4982.1  142.35  4995.6  138.77
  4999.5  136.81  5004.4  138.63  5026.5  141.29  5056.5  142.82  5136.5  144.47
  5286.5  143.27  5344.9  144.26  5434.9  143.75  5524.9  144.19  5694.9  142.62
  6244.9  143.86  6404.9  142.26  6454.9  142.64  6484.9  144.61  6535.5  146.01
#Mann= 5 ,-1 , 0
  3037.3     .99       0  4726.5     .14       0  4916.5     .06       0
  5136.5     .14       0  5434.9     .06       0
Bank Sta=4916.5,5136.5
XS Rating Curve= 0
Exp/Cntr=.3,.1

Type RM Length L Ch R = 1 ,17547.9 ,928.89,950.9,1222.11
BEGIN DESCRIPTION:
Cross Section K140-00-00-X05A; Detention ponds on right and left overbanks
END DESCRIPTION:
XS GIS Cut Line= 4
 3047863.317820713938026.3873627      3047845.85     13935183.22
      3047767.98     13934874.56      3046195.53     13933661.48
#Sta/Elev= 30
  2079.7   146.7  3269.7   145.2  3639.7   142.5  4039.7   143.1  4059.7   144.4
  4099.7     143  4339.7   143.1  4439.7   140.7  4459.7   135.2  4899.7   134.9
  4909.7   136.6  4933.5   144.7  4963.7  145.09  4968.1  142.54  4980.7  141.55
  5000.7  135.06  5014.8  141.96  5102.9     140    5200   142.4  5232.9   133.9
  5241.2   133.5  5961.2   132.3  5981.2   133.6  5991.2   139.6  6011.2     143
  6471.2   142.9  6911.2   141.9  6961.2   143.3  7061.2   141.2  7227.2   146.2
#Mann= 5 ,-1 , 0
  2079.7     .99       0  4933.5     .04       0    5200    .026       0
  6011.2     .12       0  6471.2     .99       0
#Block Obstruct= 2 ,-1
 4403.79  4933.5  142.39    5204 6009.15   142.4
Bank Sta=4963.7,5014.8
XS Rating Curve= 0
Exp/Cntr=.3,.1

Type RM Length L Ch R = 1 ,16597   ,89.2,89.2,89.2
BEGIN DESCRIPTION:
K140-00-00-S7_HUFFSMITH-KOHRVILLE -US - XS 4
END DESCRIPTION:
XS GIS Cut Line= 5
      3048552.36      13938311.3      3048746.45      13934851.5
      3048703.37      13934777.3      3048769.74      13933764.3
      3047046.36      13932326.8
#Sta/Elev= 30
  1493.4  144.81  1693.4  144.83  2603.4  143.46  3363.4  142.89  4273.4  142.48
  4333.4  147.66  4413.4  143.13  4473.4  144.57  4573.4  141.39 4923.31  141.87
 4981.51  137.69 4990.98  136.44 4993.46  134.32 5061.53   141.5 5152.76  141.57
  5304.5  140.35  5404.5  142.53  6799.6  140.08  7059.6  143.02  7089.6  142.14
  7129.6  136.79  7169.6  136.33  7209.6  136.97  7259.6  142.14  7399.6  139.62
  7729.6  141.56  7809.6  143.77  8119.6  141.82  8209.6  138.75  8279.6   152.7
#Mann= 8 ,-1 , 0
  1493.4     .99       0  1693.4     .06       0  2603.4     .14       0
  3363.4     .08       0 4923.31     .04       0 5152.76     .06       0
  5404.5     .14       0  6799.6     .99       0
Bank Sta=4923.31,5061.53
XS Rating Curve= 0
Exp/Cntr=.5,.3

Type RM Length L Ch R = 1 ,16507.8 ,76,76,76
BEGIN DESCRIPTION:
K140-00-00-S7_HUFFSMITH-KOHRVILLE -US - XS3
END DESCRIPTION:
XS GIS Cut Line= 6
      3048635.02     13938271.71 3048805.3297354     13934851.24
 3048852.3880402     13933724.74 3048263.8908576     13933233.82
 3048252.0208026     13933223.97 3047129.0099253     13932287.19
#Sta/Elev= 30
  1497.4  145.91  2287.4  144.91  2437.4  143.01  2697.4  144.51  2987.4  141.81
  3607.4  142.41  3727.4  140.51  3877.4  142.11  4067.4  139.81  4117.4  142.21
  4337.4  139.31    4626  141.57  4919.1  141.53  4990.1  136.57  4992.7  134.24
  5007.3  134.57    5010  136.33  5066.4  141.45  5104.1  141.52  5512.1  141.91
  5542.1  140.51  5992.1  142.01  6740.3  140.11  6810.3  142.91  7020.3  143.11
  7270.3  140.31  7700.3  141.11  7820.3  144.21  8240.3  139.71  8280.3  147.11
#Mann= 8 ,-1 , 0
  1497.4     .99       0    4626    .045       0  4919.1    .033       0
  4990.1     .04       0    5010    .033       0  5066.4    .045       0
  5104.1     .12       0  5512.1     .99       0
#XS Ineff= 2 , 0
       0  4909.1   141.1  5076.4       0   139.7
Permanent Ineff=
       F       F
Bank Sta=4919.1,5066.4
XS Rating Curve= 0
Exp/Cntr=.5,.3

Type RM Length L Ch R = 3 ,16469.8 ,,,
BEGIN DESCRIPTION:
HUFSMITH-KOHRVILLE
Structure ID: K140-00-00-S7
END DESCRIPTION:
Bridge Culvert--1,0,-1,-1, 0
Deck Dist Width WeirC Skew NumUp NumDn MinLoCord MaxHiCord MaxSubmerge Is_Ogee
1,71,2.6,0, 61, 61, , , .95, 0, ,,,
  3217.4  3454.7  3497.4  3508.3  3527.4  3577.4  3607.4  3647.4  3687.4  3697.4
  3727.4  3787.4  3797.4  3817.4  3827.4  3847.4  3877.4  3907.4  3917.4  3977.4
  3997.4  4067.4  4087.4  4097.4  4117.4  4177.4  4207.4  4217.4  4237.4  4257.4
  4267.4  4277.4  4287.4  4337.4  4457.4  4477.4    4626  4676.6  4736.3  4796.9
  4859.1  4919.1  4923.4 4944.89  4944.9  4954.5  4984.6  5014.5 5044.49  5054.3
 5054.31  5066.4  5104.1  5160.4  5215.9  5273.4  5322.1  5332.1  5352.1  5363.6
  5992.1
   143.3   143.5  143.44  143.43   143.4  143.33  143.29  143.24  143.18  143.17
  143.13  143.05  143.03     143  142.99  142.96  142.92  142.88  142.87  142.79
  142.76  142.66  142.64  142.62   142.6  142.51  142.47  142.46  142.43   142.4
  142.39  142.38  142.36  142.29  142.13   142.1   141.9  141.83  141.75  141.68
  141.66   141.7  141.72  141.79  145.42  146.38  146.51  146.38  146.33  145.44
  141.77  141.73  141.52  141.63  141.74  141.84  141.81  141.81   141.8   141.8
     142
          141.15   141.2  141.56   142.2   141.6   142.4     141   140.7   141.1
   140.5   141.4   142.2   141.7     141   141.3   142.1   141.6   141.7   140.3
   140.7   139.8   140.3   141.3   142.2   140.8   141.2   140.9     141   141.6
   140.4   140.2   140.6   139.3   139.8   140.8  141.56  141.82  141.75  141.67
  141.59     130     130     130     130  140.44  140.55   140.5  140.39     130
     130  141.44  141.51  141.62  141.72  141.83   141.8   141.8   141.1  141.04
        
  3217.4  3454.7  3497.4  3508.3  3527.4  3577.4  3607.4  3647.4  3687.4  3697.4
  3727.4  3787.4  3797.4  3817.4  3827.4  3847.4  3877.4  3907.4  3917.4  3977.4
  3997.4  4067.4  4087.4  4097.4  4117.4  4177.4  4207.4  4217.4  4237.4  4257.4
  4267.4  4277.4  4287.4  4337.4  4457.4  4477.4    4626  4676.6  4736.3  4796.9
  4859.1  4919.1  4923.4 4944.89  4944.9  4954.5  4984.6  5014.5 5044.49  5054.3
 5054.31  5066.4  5104.1  5160.4  5215.9  5273.4  5322.1  5332.1  5352.1  5363.6
  5992.1
  143.57   143.5  143.44  143.43   143.4  143.33  143.29  143.24  143.18  143.17
  143.13  143.05  143.03     143  142.99  142.96  142.92  142.88  142.87  142.79
  142.76  142.66  142.64  142.62   142.6  142.51  142.47  142.46  142.43   142.4
  142.39  142.38  142.36  142.29  142.13   142.1   141.9  142.09  142.02  141.94
  141.86   141.7  141.72  141.79  145.55  146.28   146.4  146.53  146.39  145.54
  141.77  141.73  141.78  141.89  141.99   142.1  142.07  142.07   141.8   141.8
  142.27
          141.42  141.47  141.83  142.47  141.87  142.67  141.27  140.97  141.37
  140.77  141.67  142.47  141.97  141.27  141.57  142.37  141.87  141.97  140.57
  140.97  140.07  140.57  141.57  142.47  141.07  141.47  141.17  141.27  141.87
  140.67  140.47  140.87  139.57  140.07  141.07  141.83  142.09  142.02  141.94
  141.86   141.7  141.67     130     130  140.45  140.51  140.45  140.39     130
     130  141.71  141.78  141.89  141.99   142.1  142.07  142.07  141.37  141.31
        
Pier Skew, UpSta & Num, DnSta & Num=  ,4984.6, 4 ,4984.6, 4 , 3 , 3 , 0 ,,
     1.3     1.3       2       2
  135.88  138.65  138.65  140.55
     1.3     1.3       2       2
  136.15  138.61  138.61  140.51
Pier Skew, UpSta & Num, DnSta & Num=  ,5014.5, 4 ,5014.5, 4 , 3 , 3 , 0 ,,
     1.3     1.3       2       2
  135.49   138.6   138.6   140.5
     1.3     1.3       2       2
  135.76  138.55  138.55  140.45
BR Coef= 1 , 1 , 1 ,.9, 0 ,,,.8,-1,1.2,0,
WSPro=,,,, 1 ,,,, 0 ,,,, 0 ,,,,-1 ,-1 ,-1 , 0 , 0 , 0 , 0 , 0
BR U #Sta/Elev= 185
   107.4   146.5   137.4   147.1   167.4   146.6   427.4   146.3   557.4   145.4
   657.4   145.9   697.4   145.5   707.4   145.7   767.4   145.6   837.4   145.7
   857.4   145.1  1087.4   145.2  1157.4   145.6  1387.4   145.6  1417.4   144.9
  1497.4   145.9  1697.4   144.5  1777.4   144.7  1787.4   144.4  1837.4   144.8
  2087.4     144  2287.4   144.9  2327.4   143.8  2417.4   143.5  2437.4     143
  2447.4   143.1  2467.4   143.9  2537.4   143.2  2567.4   143.7  2607.4   143.5
  2627.4   144.6  2647.4   144.6  2677.4   144.3  2697.4   144.5  2707.4   143.8
  2747.4   142.9  2837.4   143.1  2857.4   142.9  2867.4   143.2  2887.4   142.9
  2917.4   143.2  2927.4   142.6  2947.4   142.6  2987.4   141.8  3217.4   143.3
  3287.4     142  3307.4   142.9  3327.4   142.7  3337.4   142.2  3347.4   142.3
  3357.4     143  3417.4   141.1  3454.7  141.15  3497.4   141.2  3508.3  141.56
  3527.4   142.2  3577.4   141.6  3607.4   142.4  3647.4     141  3687.4   140.7
  3697.4   141.1  3727.4   140.5  3787.4   141.4  3797.4   142.2  3817.4   141.7
  3827.4     141  3847.4   141.3  3877.4   142.1  3907.4   141.6  3917.4   141.7
  3977.4   140.3  3997.4   140.7  4067.4   139.8  4087.4   140.3  4097.4   141.3
  4117.4   142.2  4177.4   140.8  4207.4   141.2  4217.4   140.9  4237.4     141
  4257.4   141.6  4267.4   140.4  4277.4   140.2  4287.4   140.6  4337.4   139.3
  4457.4   139.8  4477.4   140.8    4626  141.56  4676.6  141.82  4736.3  141.75
  4796.9  141.67  4859.1  141.59  4919.1  141.52  4923.4   141.4  4948.7  140.71
 4954.29  140.19  4954.4  140.18 4954.51  140.17 4960.01  139.66  4960.1  139.65
  4982.4  137.57  4984.6  136.92  4990.1  136.56  4992.7  134.23  5007.3  134.56
    5010  136.32  5014.5  136.52    5023  138.09 5044.49  140.16  5044.6  140.17
 5044.71  140.18  5045.2  140.23 5046.96  140.33 5049.89   140.5    5050   140.5
  5050.1  140.51  5066.4  141.44  5104.1  141.51  5160.4  141.62  5215.9  141.72
  5273.4  141.83  5322.1   141.8  5332.1   141.8  5352.1   141.1  5363.6  141.04
  5392.1   140.9 5402.03   141.5  5402.1   141.5  5432.1   141.4  5452.1   142.5
  5462.1   142.7  5482.1   141.4  5512.1   141.9  5542.1   140.5  5612.1   140.4
  5642.1   141.2  5702.1   141.2  5722.1   141.8  5852.1   141.7  5872.1   140.7
  5892.1   140.7  5992.1     142  6012.1   141.3  6022.1   140.6  6080.3     141
  6100.3   141.6  6120.3     141  6230.3   141.2  6250.3   140.5  6350.3   140.8
  6390.3   140.3  6420.3     141  6440.3   140.4  6690.3   140.3  6710.3   141.1
  6720.3   141.2  6740.3   140.1  6750.3   140.7  6760.3   140.4  6780.3   142.2
  6810.3   142.9  6990.3   142.6  7020.3   143.1  7050.3   142.8  7080.3   141.2
  7090.3   142.6  7110.3   141.1  7140.3   141.7  7160.3   141.1  7260.3   140.6
  7270.3   140.3  7610.3   141.3  7700.3   141.1  7820.3   144.2  8110.3   142.2
  8200.3     140  8230.3   140.7  8240.3   139.7  8250.3   140.7  8280.3   147.1
  8310.3     154  8320.3   155.8  8340.3   156.8  8390.3   158.1  8411.8   157.9
BR U #Mann= 8
   107.4     .99  4859.1    .045  4919.1     .04 4954.51    .017 5046.96     .04
  5066.4    .045  5104.1     .12  5273.4     .99
BR U Banks=4919.1,5066.4
BR D #Sta/Elev= 185
   107.4  146.77   137.4  147.37   167.4  146.87   427.4  146.57   557.4  145.67
   657.4  146.17   697.4  145.77   707.4  145.97   767.4  145.87   837.4  145.97
   857.4  145.37  1087.4  145.47  1157.4  145.87  1387.4  145.87  1417.4  145.17
  1497.4  146.17  1697.4  144.77  1777.4  144.97  1787.4  144.67  1837.4  145.07
  2087.4  144.27  2287.4  145.17  2327.4  144.07  2417.4  143.77  2437.4  143.27
  2447.4  143.37  2467.4  144.17  2537.4  143.47  2567.4  143.97  2607.4  143.77
  2627.4  144.87  2647.4  144.87  2677.4  144.57  2697.4  144.77  2707.4  144.07
  2747.4  143.17  2837.4  143.37  2857.4  143.17  2867.4  143.47  2887.4  143.17
  2917.4  143.47  2927.4  142.87  2947.4  142.87  2987.4  142.07  3217.4  143.57
  3287.4  142.27  3307.4  143.17  3327.4  142.97  3337.4  142.47  3347.4  142.57
  3357.4  143.27  3417.4  141.37  3454.7  141.42  3497.4  141.47  3508.3  141.83
  3527.4  142.47  3577.4  141.87  3607.4  142.67  3647.4  141.27  3687.4  140.97
  3697.4  141.37  3727.4  140.77  3787.4  141.67  3797.4  142.47  3817.4  141.97
  3827.4  141.27  3847.4  141.57  3877.4  142.37  3907.4  141.87  3917.4  141.97
  3977.4  140.57  3997.4  140.97  4067.4  140.07  4087.4  140.57  4097.4  141.57
  4117.4  142.47  4177.4  141.07  4207.4  141.47  4217.4  141.17  4237.4  141.27
  4257.4  141.87  4267.4  140.67  4277.4  140.47  4287.4  140.87  4337.4  139.57
  4457.4  140.07  4477.4  141.07    4626  141.83  4676.6  142.09  4736.3  142.02
  4796.9  141.94  4859.1  141.86  4919.1  141.79  4923.4  141.67  4948.7  140.98
 4954.29  140.46  4954.4  140.45 4954.51  140.44 4960.01  139.93  4960.1  139.92
  4982.4  137.84  4984.6  137.19  4990.1  136.83  4992.7   134.5  5007.3  134.83
    5010  136.59  5014.5  136.79    5023  138.36 5044.49  140.43  5044.6  140.44
 5044.71  140.45  5045.2   140.5 5046.96   140.6 5049.89  140.77    5050  140.77
  5050.1  140.78  5066.4  141.71  5104.1  141.78  5160.4  141.89  5215.9  141.99
  5273.4   142.1  5322.1  142.07  5332.1  142.07  5352.1  141.37  5363.6  141.31
  5392.1  141.17 5402.03  141.77  5402.1  141.77  5432.1  141.67  5452.1  142.77
  5462.1  142.97  5482.1  141.67  5512.1  142.17  5542.1  140.77  5612.1  140.67
  5642.1  141.47  5702.1  141.47  5722.1  142.07  5852.1  141.97  5872.1  140.97
  5892.1  140.97  5992.1  142.27  6012.1  141.57  6022.1  140.87  6080.3  141.27
  6100.3  141.87  6120.3  141.27  6230.3  141.47  6250.3  140.77  6350.3  141.07
  6390.3  140.57  6420.3  141.27  6440.3  140.67  6690.3  140.57  6710.3  141.37
  6720.3  141.47  6740.3  140.37  6750.3  140.97  6760.3  140.67  6780.3  142.47
  6810.3  143.17  6990.3  142.87  7020.3  143.37  7050.3  143.07  7080.3  141.47
  7090.3  142.87  7110.3  141.37  7140.3  141.97  7160.3  141.37  7260.3  140.87
  7270.3  140.57  7610.3  141.57  7700.3  141.37  7820.3  144.47  8110.3  142.47
  8200.3  140.27  8230.3  140.97  8240.3  139.97  8250.3  140.97  8280.3  147.37
  8310.3  154.27  8320.3  156.07  8340.3  157.07  8390.3  158.37  8411.8  158.17
BR D #Mann= 8
   107.4     .99  4859.1    .045  4919.1     .04 4954.51    .017 5046.96     .04
  5066.4    .045  5104.1     .12  5273.4     .99
BR D Banks=4919.1,5066.4
BC Design=,, 0 ,, 0 ,,,,,,
BC HTab HWMax=147.11

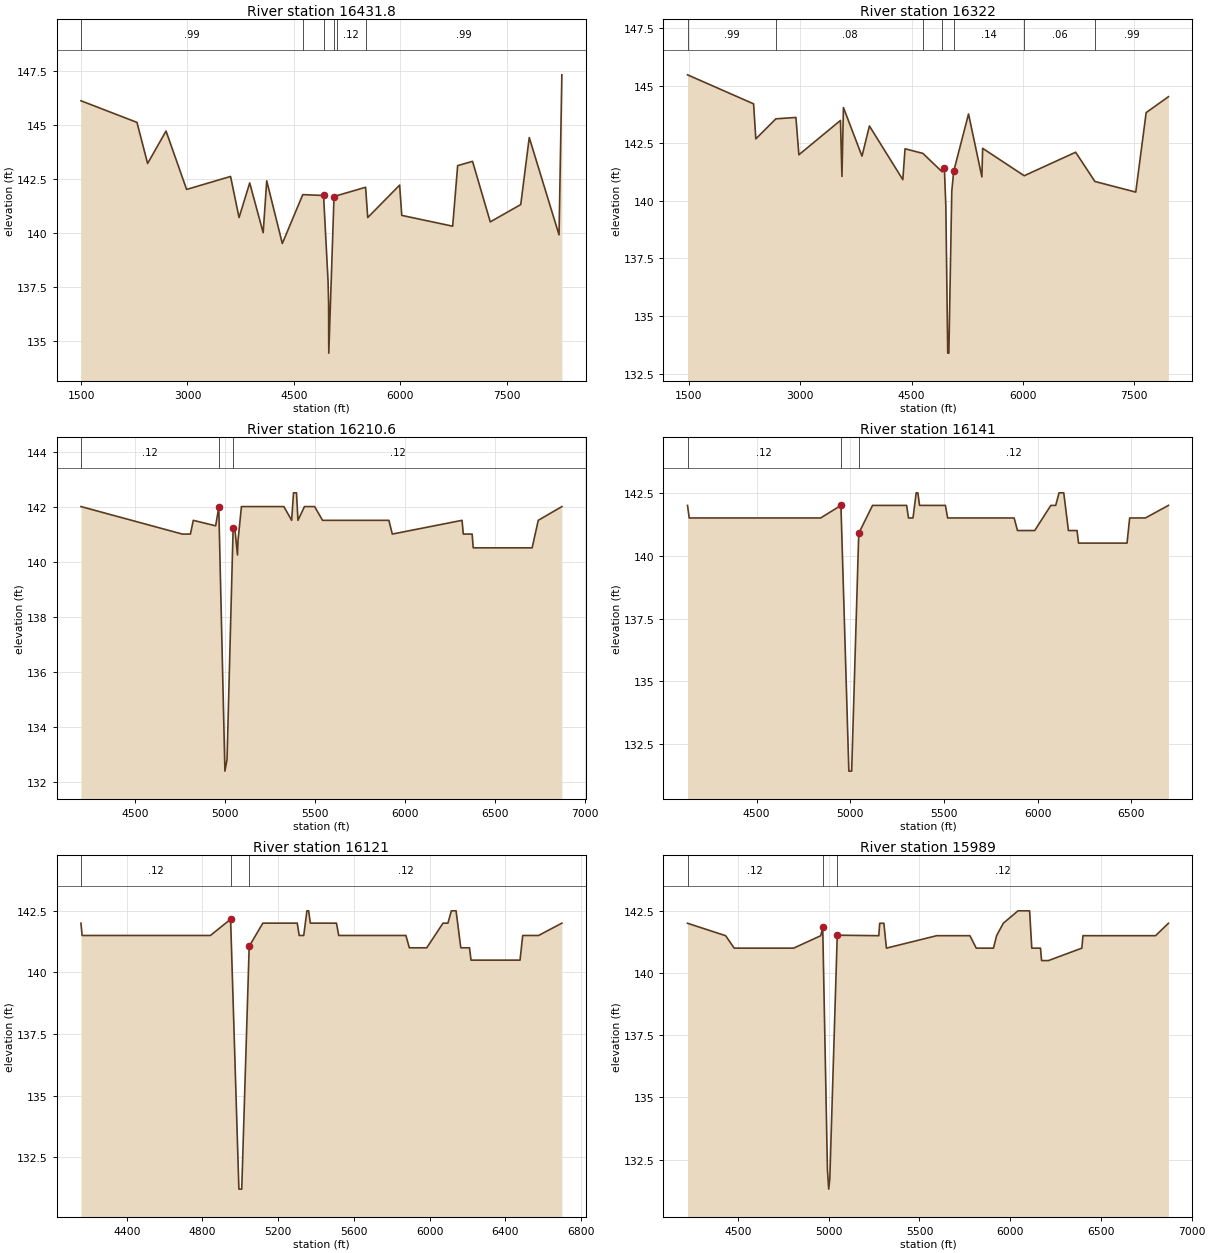
Type RM Length L Ch R = 1 ,16431.8 ,137.87,109.8,47.49
BEGIN DESCRIPTION:
K140-00-00-S7_HUFFSMITH-KOHRVILLE DS - XS2
END DESCRIPTION:
XS GIS Cut Line= 6
      3048702.16      13938254.6 3048872.4929868     13934833.77
  3048921.151026     13933690.34 3047330.0734995      13932370.7
 3047309.0233447     13932353.62 3047188.9914326     13932253.68
#Sta/Elev= 30
  1497.4  146.13  2287.4  145.13  2437.4  143.23  2697.4  144.73  2987.4  142.03
  3607.4  142.63  3727.4  140.73  3877.4  142.33  4067.4  140.03  4117.4  142.43
  4337.4  139.53    4626  141.79  4919.1  141.75  4982.4   137.8  4990.1  136.79
  4992.7  134.46  5066.4  141.67  5104.1  141.74  5512.1  142.13  5542.1  140.73
  5992.1  142.23  6022.1  140.83  6740.3  140.33  6810.3  143.13  7020.3  143.33
  7270.3  140.53  7700.3  141.33  7820.3  144.43  8240.3  139.93  8280.3  147.33
#Mann= 6 ,-1 , 0
  1497.4     .99       0    4626    .045       0  4919.1     .04       0
  5066.4    .045       0  5104.1     .12       0  5512.1     .99       0
#XS Ineff= 2 , 0
       0 4912.43   141.1 5073.07       0   139.7
Permanent Ineff=
       F       F
Bank Sta=4919.1,5066.4
XS Rating Curve= 0
Exp/Cntr=.5,.3

Type RM Length L Ch R = 1 ,16322   ,179,181,147
BEGIN DESCRIPTION:
K140-00-00-S7_HUFFSMITH-KOHRVILLE DS - XS 1
END DESCRIPTION:
XS GIS Cut Line= 5
      3048799.11      13938205.6       3048995.4      13934748.6
      3048961.89      13934662.4      3049018.11      13933641.4
 3047555.632994913932428.3963207
#Sta/Elev= 30
  1481.5  145.47  2371.5  144.21  2401.5  142.69  2671.5  143.56  2941.5  143.62
  2981.5     142  3541.5  143.49  3561.5  141.06  3581.5  144.05  3831.5  141.94
  3931.5  143.25  4381.5  140.92  4411.5  142.26  4651.5  142.06  4911.5  141.26
  4941.5  141.41 4961.01  139.76  4986.5  133.39  5001.5  133.39    5041  140.42
  5066.6  141.28  5266.6  143.77  5446.6  141.04  5456.6  142.28  6016.6  141.09
  6709.2  142.11  6969.2  140.84  7519.2  140.38  7659.2  143.83  7959.2  144.52
#Mann= 7 ,-1 , 0
  1481.5     .99       0  2671.5     .08       0  4651.5     .14       0
  4911.5     .04       0  5066.6     .14       0  6016.6     .06       0
  6969.2     .99       0
Bank Sta=4941.5,5066.6
XS Rating Curve= 0
Exp/Cntr=.3,.1

Type RM Length L Ch R = 1 ,16210.6 ,82,90,64
XS GIS Cut Line= 6
   3049431.14044  13935366.14044   3049192.26379  13934857.26379
   3049029.60114  13934574.60205       3048997.5   13934341.3916
   3049020.31169  13933638.25312       3048517.5  13933199.77112
#Sta/Elev= 30
  4201.1     142  4763.8     141  4808.7     141  4824.4   141.5 4948.51   141.3
 4965.96  141.97    5000  132.38  5011.7   132.8 5045.59  141.21 5056.82  141.08
  5069.7  140.24 5072.63  140.76 5091.73     142 5327.13     142 5370.43   141.5
 5380.73   142.5 5397.23   142.5 5405.43   141.5 5441.53     142 5497.73     142
 5541.93   141.5    5910   141.5    5929     141    6316   141.5    6323     141
    6372     141    6378   140.5    6705   140.5    6739   141.5    6870     142
#Mann= 3 , 0 , 0
  4201.1     .12       0 4965.96     .04       0 5045.59     .12       0
Bank Sta=4965.96,5045.59
XS Rating Curve= 0
Exp/Cntr=.3,.1

Type RM Length L Ch R = 1 ,16141   ,20,20,20
XS GIS Cut Line= 5
   3049471.42852  13935378.19528      3049352.77     13935109.08
      3049015.13     13934357.25      3049029.75     13933639.76
      3048502.96     13933173.46
#Sta/Elev= 30
    4131     142    4140   141.5    4842   141.5 4950.22     142  4992.5  131.43
  5007.5  131.43 5045.35  140.89    5119     142    5301     142    5311   141.5
    5335   141.5    5352   142.5    5361   142.5    5370     142    5508     142
    5520   141.5    5875   141.5    5893     141    5985     141    6071     142
    6097     142    6115   142.5    6140   142.5    6165     141    6211     141
    6219   140.5    6478   140.5    6492   141.5    6576   141.5    6699     142
#Mann= 3 , 0 , 0
    4131     .12       0 4950.22     .04       0 5045.35     .12       0
Bank Sta=4950.22,5045.35
XS Rating Curve= 0
Exp/Cntr=.3,.1

Type RM Length L Ch R = 1 ,16121   ,143,132,84
XS GIS Cut Line= 5
   3049489.58953  13935378.35572       3049385.8      13935133.5
      3049039.95     13934346.17      3049044.75     13933633.87
      3048527.78     13933162.38
#Sta/Elev= 30
    4158     142    4164   141.5    4842   141.5 4948.68  142.16  4992.5  131.21
  5007.5  131.21 5046.91  141.06    5119     142    5301     142    5311   141.5
    5335   141.5    5352   142.5    5361   142.5    5370     142    5508     142
    5520   141.5    5875   141.5    5893     141    5985     141    6071     142
    6097     142    6115   142.5    6140   142.5    6165     141    6211     141
    6219   140.5    6478   140.5    6492   141.5    6576   141.5    6699     142
#Mann= 3 , 0 , 0
    4158     .12       0 4948.68     .04       0 5046.91     .12       0
Bank Sta=4948.68,5046.91
XS Rating Curve= 0
Exp/Cntr=.3,.1

Type RM Length L Ch R = 1 ,15989   ,63,57,42
XS GIS Cut Line= 6
   3049696.23871  13935121.23871      3049296.37     13934567.76
      3049196.35     13934488.07      3049131.93     13934352.33
      3049052.23     13933631.05   3048467.49847  13933092.50061
#Sta/Elev= 30
    4222     142    4432   141.5    4479     141    4807     141    4956   141.5
    4967  141.84    4993  132.08    5000  131.31    5006  131.72    5047  141.52
    5276   141.5    5281     142    5304     142    5318     141    5595   141.5
    5778   141.5    5813     141    5908     141    5925   141.5    5962     142
    6043   142.5    6107   142.5    6119     141    6167     141    6173   140.5
    6211   140.5    6395     141    6401   141.5    6801   141.5    6872     142
#Mann= 3 , 0 , 0
    4222     .12       0    4967     .04       0    5047     .12       0
Bank Sta=4967,5047
XS Rating Curve= 0
Exp/Cntr=.3,.1

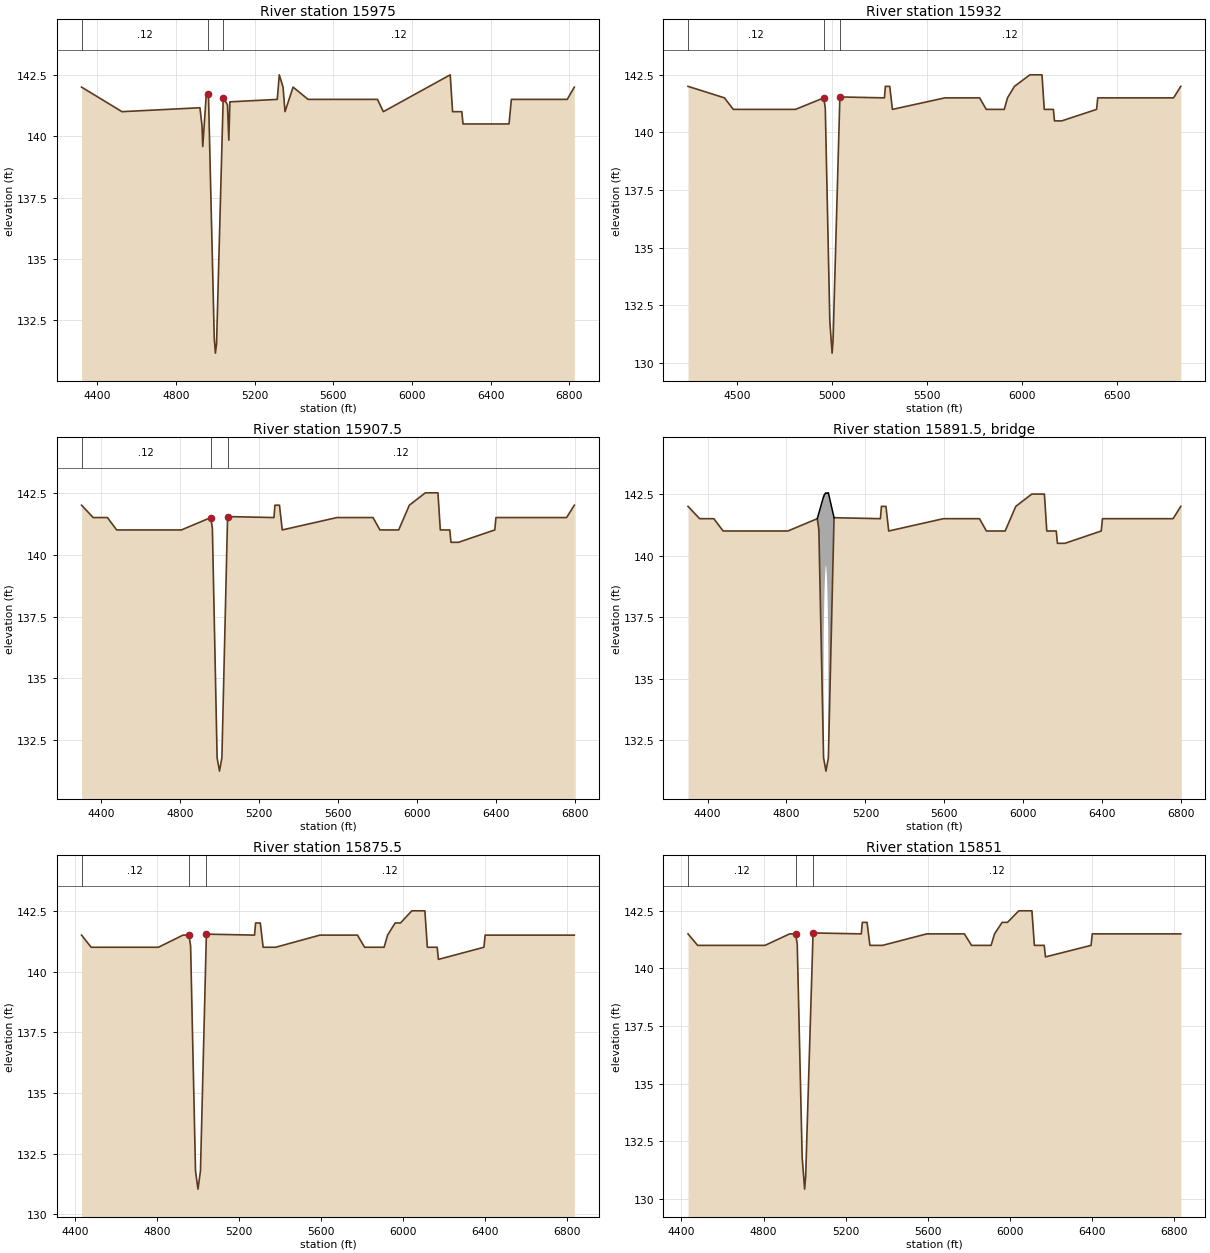
Type RM Length L Ch R = 1 ,15975   ,40,43,43
XS GIS Cut Line= 6
       3049702.5  13935062.46094   3049336.75084  13934586.95341
    3049213.8106  13934484.21566   3049141.33392  13934308.66699
   3049055.20131  13933630.04152   3048467.74181  13933090.31815
#Sta/Elev= 30
 4319.28     142 4524.84     141 4921.34  141.16 4931.66  140.44 4935.54  139.58
 4954.22  141.77 4964.58  141.71 4994.04  131.78    5000  131.17 5005.87  131.56
 5039.63  141.57 5061.28  141.28 5068.16  139.84 5073.59   141.4 5314.53   141.5
 5324.73   142.5 5343.93     142 5353.83     141 5395.03     142 5471.13   141.5
    5824   141.5    5854     141    6194   142.5    6206     141    6253     141
    6259   140.5    6493   140.5    6505   141.5    6789   141.5    6825     142
#Mann= 3 , 0 , 0
 4319.28     .12       0 4964.58     .04       0 5039.63     .12       0
Bank Sta=4964.58,5039.63
XS Rating Curve= 0
Exp/Cntr=.3,.1

Type RM Length L Ch R = 1 ,15932   ,25,24.5,27
XS GIS Cut Line= 6
   3049712.46735  13935047.46735   3049329.61415   13934508.9739
   3049228.00785  13934463.77906   3049170.11637  13934348.57236
   3049058.08541  13933628.12303   3048468.05603      13933087.5
#Sta/Elev= 30
    4240     142    4432   141.5    4479     141    4807     141    4956   141.5
    4964  141.06    4988  131.79    5000  130.42    5005  130.97    5041  141.54
    5276   141.5    5281     142    5304     142    5318     141    5595   141.5
    5778   141.5    5813     141    5908     141    5925   141.5    5962     142
    6043   142.5    6107   142.5    6119     141    6167     141    6173   140.5
    6211   140.5    6395     141    6401   141.5    6801   141.5    6839     142
#Mann= 3 , 0 , 0
    4240     .12       0    4956     .04       0    5041     .12       0
Bank Sta=4956,5041
XS Rating Curve= 0
Exp/Cntr=.3,.1

Type RM Length L Ch R = 1 ,15907.5 ,32,32,32
XS GIS Cut Line= 6
   3049709.22272      13935007.5   3049345.13097  13934488.55628
   3049246.15234  13934445.32179   3049193.73454  13934341.00795
    3049062.0654  13933624.68149   3048472.06554   13933086.8303
#Sta/Elev= 30
    4301     142    4360   141.5    4432   141.5    4479     141    4807     141
    4956   141.5    4964  141.06 4987.93  131.79    5000  131.25 5012.18  131.79
    5041  141.54    5276   141.5    5281     142    5304     142    5318     141
    5595   141.5    5778   141.5    5813     141    5908     141    5962     142
    6043   142.5    6107   142.5    6119     141    6167     141    6173   140.5
    6211   140.5    6395     141    6401   141.5    6759   141.5    6798     142
#Mann= 3 , 0 , 0
    4301     .12       0    4956     .04       0    5041     .12       0
Bank Sta=4956,5041
XS Rating Curve= 0
Exp/Cntr=.3,.1

Type RM Length L Ch R = 3 ,15891.5 ,,,
Bridge Culvert--1,0,-1,-1, 0
Deck Dist Width WeirC Skew NumUp NumDn MinLoCord MaxHiCord MaxSubmerge Is_Ogee
1,30,2.6,0, 22, 22, , , .95, 0, 0,0,,
    4956 4987.84 4987.91 4988.03  4988.4 4988.91 4990.09 4991.82 4993.75 4995.57
  4997.4 4999.63 5001.79  5004.6 5006.91 5009.13 5010.74 5011.54 5011.95 5012.15
 5012.18    5041
   141.5   142.4   142.4   142.4  142.41  142.41  142.42  142.48   142.5  142.51
  142.53  142.55  142.53  142.53  142.53  142.55  142.55  142.55  142.55  142.55
  142.55  141.54
   141.5  129.63  129.63  135.54  136.31  136.91  137.57  138.23   138.8  139.19
  139.45  139.63  139.52  139.18  138.67  137.93   137.2  136.52  135.79  135.12
   131.7     133
    4956 4987.84 4987.91 4988.03  4988.4 4988.91 4990.09 4991.82 4993.75 4995.57
  4997.4 4999.63 5001.79  5004.6 5006.91 5009.13 5010.74 5011.54 5011.95 5012.15
 5012.18    5041
   141.5   142.4   142.4   142.4  142.41  142.41  142.42  142.48   142.5  142.51
  142.53  142.55  142.53  142.53  142.53  142.55  142.55  142.55  142.55  142.55
  142.55  141.54
   141.5  129.63  129.63  135.54  136.31  136.91  137.57  138.23   138.8  139.19
  139.45  139.63  139.52  139.18  138.67  137.93   137.2  136.52  135.79  135.12
   131.7     133
BR Coef=-1 , 0 , 0 ,, 0 ,,,.8,-1,,0,
WSPro=,,,, 1 ,,,, 0 ,,,, 0 ,,,,-1 ,-1 ,-1 , 0 , 0 , 0 , 0 , 0
BC Design=,, 0 ,, 0 ,,,,,,

Type RM Length L Ch R = 1 ,15875.5 ,28,24.5,20
XS GIS Cut Line= 6
      3049639.54     13934876.93      3049334.62     13934450.76
   3049246.35703  13934409.48135   3049192.03394  13934300.97946
    3049068.9247  13933622.85025   3048476.32324  13933083.67676
#Sta/Elev= 30
    4432   141.5    4479     141    4807     141    4927   141.5    4956   141.5
    4964  141.06 4987.93  131.79    5000  131.04 5012.18  131.79    5041  141.54
    5276   141.5    5281     142    5304     142    5318     141    5379     141
    5595   141.5    5778   141.5    5813     141    5908     141    5925   141.5
    5962     142    5988     142    6043   142.5    6107   142.5    6119     141
    6167     141    6173   140.5    6395     141    6401   141.5    6836   141.5
#Mann= 3 , 0 , 0
    4432     .12       0    4956     .04       0    5041     .12       0
Bank Sta=4956,5041
XS Rating Curve= 0
Exp/Cntr=.3,.1

Type RM Length L Ch R = 1 ,15851   ,230,261.5,306
XS GIS Cut Line= 6
      3049659.46     13934862.67      3049350.14     13934430.34
    3049248.5308  13934385.14277   3049190.63938  13934269.93607
   3049075.56869   13933620.1614   3048480.14088  13933083.86735
#Sta/Elev= 30
    4432   141.5    4479     141    4807     141    4927   141.5    4956   141.5
    4964  141.06    4988  131.79    5000  130.42    5005  130.97    5041  141.54
    5276   141.5    5281     142    5304     142    5318     141    5379     141
    5595   141.5    5778   141.5    5813     141    5908     141    5925   141.5
    5962     142    5988     142    6043   142.5    6107   142.5    6119     141
    6167     141    6173   140.5    6395     141    6401   141.5    6832   141.5
#Mann= 3 , 0 , 0
    4432     .12       0    4956     .04       0    5041     .12       0
Bank Sta=4956,5041
XS Rating Curve= 0
Exp/Cntr=.3,.1