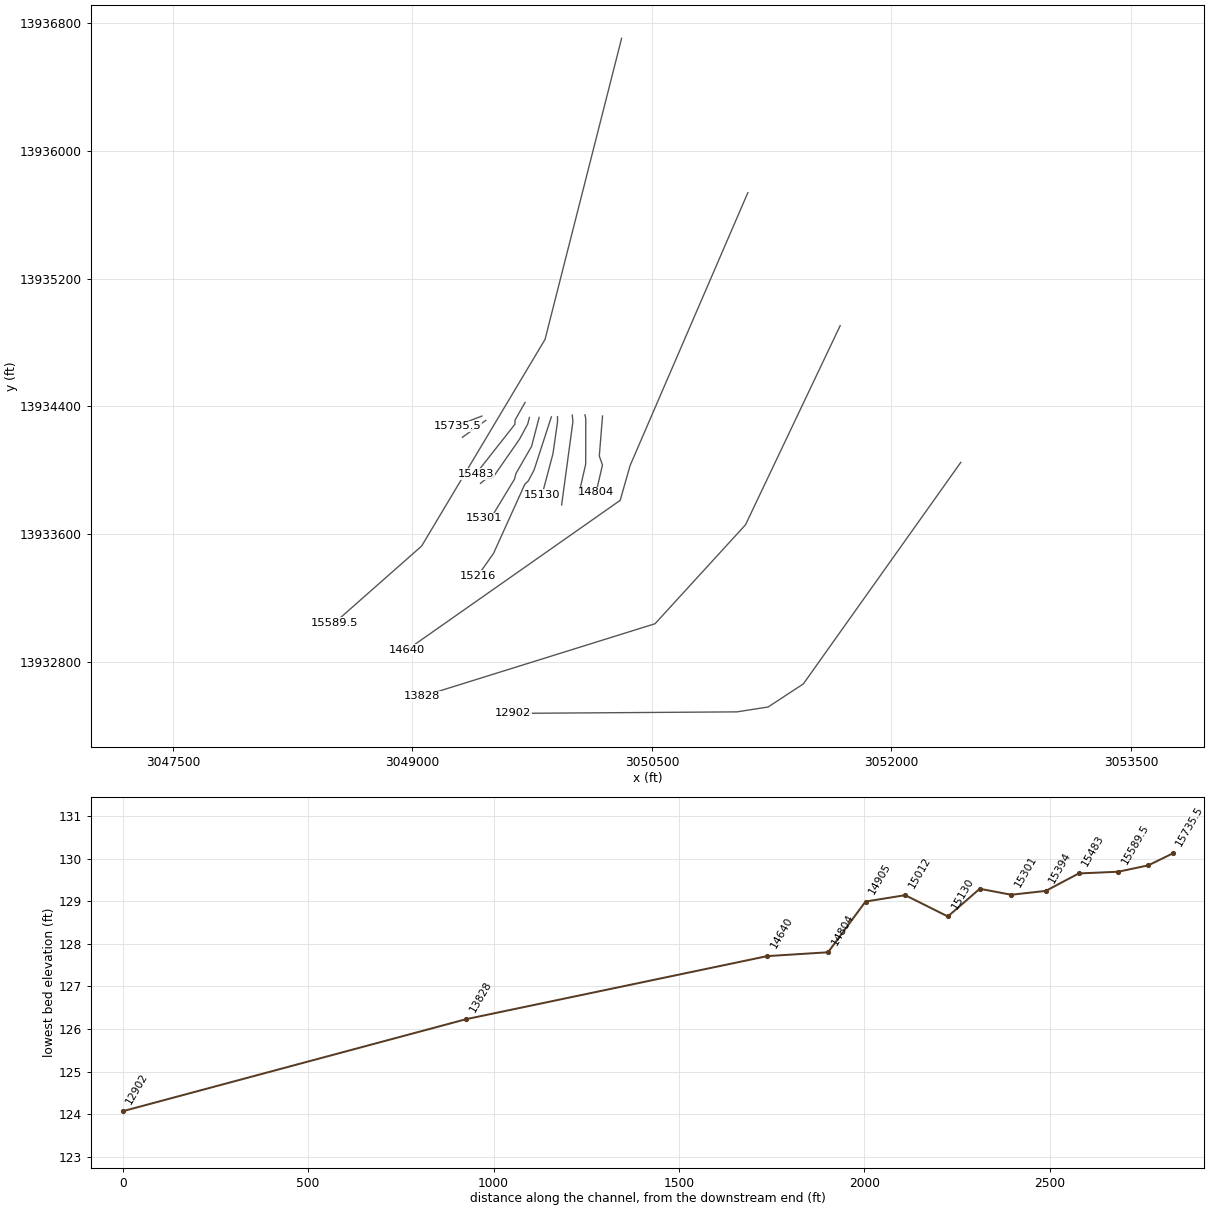
HEC-RAS study K140-00-00.prj: K140-00-00

--- K140-00-00.g01 (geometry) --- (continued)

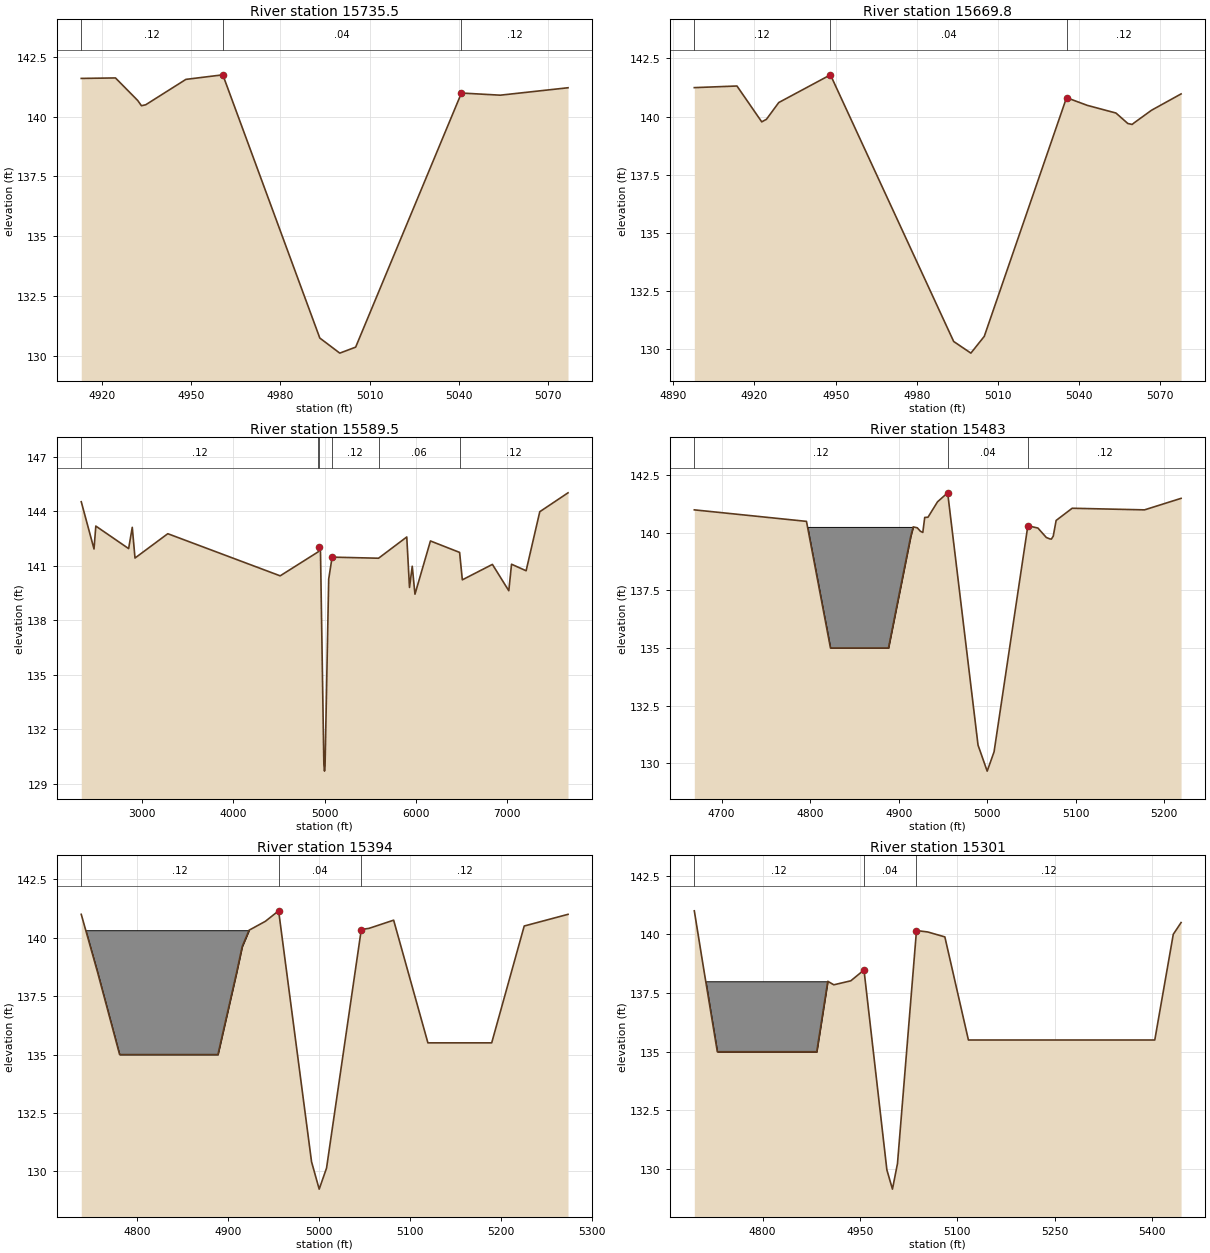
Type RM Length L Ch R = 1 ,15735.5 ,54,66,74
XS GIS Cut Line= 3
   3049434.87257  13934340.15944   3049315.36331  13934294.10494
   3049283.84359  13934277.05915
#Sta/Elev= 13
 4913.04  141.59 4924.55  141.61 4932.02  140.67 4933.29  140.45 4934.73  140.49
 4948.25  141.55 4960.66  141.74 4993.28  130.75    5000  130.12 5005.34  130.37
 5040.92  140.98 5053.97  140.89 5076.77   141.2
#Mann= 3 , 0 , 0
 4913.04     .12       0 4960.66     .04       0 5040.92     .12       0
Bank Sta=4960.66,5040.92
XS Rating Curve= 0
Exp/Cntr=.3,.1

Type RM Length L Ch R = 1 ,15669.8 ,73,81,92
XS GIS Cut Line= 2
    3049458.8197  13934312.68951   3049313.04848  13934207.47725
#Sta/Elev= 18
 4897.76  141.24 4913.53  141.31 4922.69  139.77 4923.46  139.82 4924.42  139.88
 4928.98   140.6 4948.08  141.79 4993.64  130.34    5000  129.84 5004.95  130.56
 5035.36  140.81    5043  140.48 5053.62  140.15 5058.02   139.7  5059.6  139.66
  5060.6  139.75 5066.79  140.27  5077.7  140.97
#Mann= 3 , 0 , 0
 4897.76     .12       0 4948.08     .04       0 5035.36     .12       0
Bank Sta=4948.08,5035.36
XS Rating Curve= 0
Exp/Cntr=.3,.1

Type RM Length L Ch R = 1 ,15589.5 ,106.5,106.5,106.5
BEGIN DESCRIPTION:
Interpolated XS
END DESCRIPTION:
XS GIS Cut Line= 4
       3050309.9       13936703.      3049830.34     13934819.69
       3049057.5  13933526.99524   3048512.83264  13933047.16736
#Sta/Elev= 30
  2329.9  144.52  2469.9  141.92  2489.9  143.18  2849.9  141.94  2889.9  143.11
  2919.9  141.42  3279.9  142.76  4513.4  140.44  4933.4  141.77  4943.4  142.03
    4956  141.75    4993  130.06    5000  129.69    5006  129.97    5046  140.26
  5083.4  141.47  5593.4  141.41  5902.9  142.58  5932.9   139.8  5962.9  140.97
  5992.9  139.43  6162.9  142.36  6482.9  141.73  6512.9  140.22  6842.9  141.07
  7022.9  139.62  7052.9  141.08  7212.9  140.72  7362.9  143.97  7672.9  145.01
#Mann= 6 ,-1 , 0
  2329.9     .12       0  4933.4    .045       0  4943.4     .04       0
  5083.4     .12       0  5593.4     .06       0  6482.9     .12       0
Bank Sta=4943.4,5083.4
XS Rating Curve= 0
Exp/Cntr=.3,.1

Type RM Length L Ch R = 1 ,15483   ,98,89,93
XS GIS Cut Line= 4
    3049705.1239   13934425.1239       3049642.5  13934315.03174
   3049641.45996  13934288.54004   3049396.92902  13933978.07007
#Sta/Elev= 26
 4669.15     141 4795.85   140.5 4822.95     135 4888.45     135 4913.55  139.84
 4916.38  140.26 4921.04  140.22 4924.53  140.07 4927.27  140.02 4929.43  140.67
 4933.12  140.68 4943.89  141.35 4955.34  141.74 4989.66  130.78    5000  129.65
 5007.77  130.49 5045.93  140.31 5057.28  140.21 5066.78   139.8 5070.66  139.74
 5072.52  139.73 5074.62  139.86 5077.88  140.54 5096.01  141.07 5177.71     141
 5219.01   141.5
#Mann= 3 , 0 , 0
 4669.15     .12       0 4955.34     .04       0 5045.93     .12       0
#Block Obstruct= 2 , 0
       0 4916.38  140.26               0
Bank Sta=4955.34,5045.93
XS Rating Curve= 0
Exp/Cntr=.3,.1

Type RM Length L Ch R = 1 ,15394   ,91,93,130
XS GIS Cut Line= 6
       3049732.5  13934331.28967   3049722.05017  13934290.82928
   3049670.61676  13934195.61584   3049499.07257  13933949.07166
   3049463.24066  13933949.07166   3049425.97778  13933919.02222
#Sta/Elev= 19
 4738.14     141 4756.24   138.5 4780.34     135 4888.54     135 4909.04   138.5
 4915.24  139.62 4922.82  140.32 4940.72   140.7 4955.35  141.15 4991.59  130.41
    5000  129.24 5008.09  130.14 5046.33  140.35 5054.83   140.4 5081.94  140.75
 5119.64   135.5 5189.84   135.5 5225.64   140.5 5273.84     141
#Mann= 3 , 0 , 0
 4738.14     .12       0 4955.35     .04       0 5046.33     .12       0
#Block Obstruct= 2 , 0
       0 4922.82  140.32 5081.94       0  140.75
Bank Sta=4955.35,5046.33
XS Rating Curve= 0
Exp/Cntr=.3,.1

Type RM Length L Ch R = 1 ,15301   ,70,85,105
XS GIS Cut Line= 6
   3049793.36151  13934331.63757   3049746.32263  13934151.32263
   3049648.31536   13933980.8809   3049639.21692  13933945.78308
   3049490.37231  13933700.37231   3049450.21271  13933699.78821
#Sta/Elev= 18
 4694.84     141 4709.44   138.5 4730.27     135 4883.37     135 4900.37     138
 4909.67  137.85 4935.84  138.02 4956.16  138.48  4991.4  129.97    5000  129.15
 5007.74  130.24    5037  140.16  5054.3   140.1 5080.67  139.89 5116.97   135.5
 5403.97   135.5 5432.47     140 5444.47   140.5
#Mann= 3 , 0 , 0
 4694.84     .12       0 4956.16     .04       0    5037     .12       0
#Block Obstruct= 2 , 0
       0 4900.37     138 5080.67       0  139.89
Bank Sta=4956.16,5037
XS Rating Curve= 0
Exp/Cntr=.3,.1

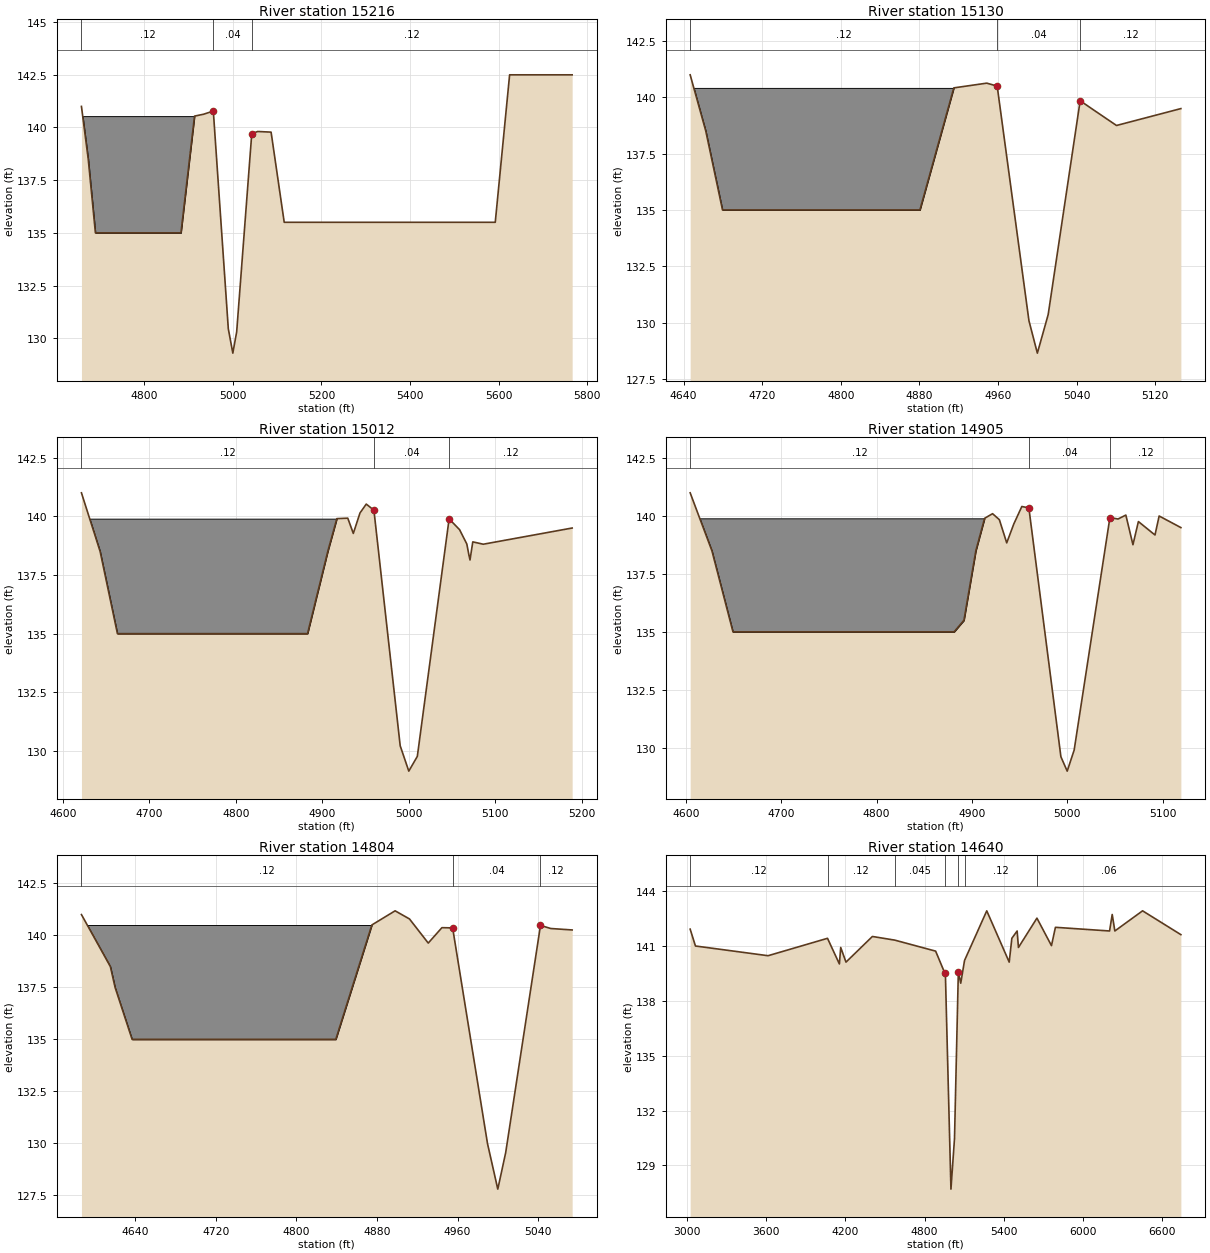
Type RM Length L Ch R = 1 ,15216   ,79,86,202
XS GIS Cut Line= 6
   3049869.81262  13934334.81262   3049761.72795  13934002.90896
   3049725.41614  13933934.30375   3049703.90167  13933913.90259
       3049507.5   13933480.5249   3049409.86267      13933342.5
#Sta/Elev= 18
  4658.5     141  4673.8   138.5    4690     135    4883     135  4913.6  140.54
 4934.12  140.63    4956  140.78 4989.79  130.45    5000  129.29  5008.7   130.3
 5042.73  139.71 5056.19  139.81 5086.34  139.78 5115.94   135.5 5375.84   135.5
 5592.04   135.5 5624.44   142.5 5765.54   142.5
#Mann= 3 , 0 , 0
  4658.5     .12       0    4956     .04       0 5042.73     .12       0
#Block Obstruct= 2 , 0
       0  4913.6  140.54 5086.34       0  139.78
Bank Sta=4956,5042.73
XS Rating Curve= 0
Exp/Cntr=.3,.1

Type RM Length L Ch R = 1 ,15130   ,101,115,123
XS GIS Cut Line= 4
   3049908.34717  13934336.65283   3049908.51379  13934303.98499
    3049880.0885   13934105.0885   3049811.70868  13933848.29224
#Sta/Elev= 14
  4646.7     141  4662.6   138.5  4679.6     135  4880.5     135    4915  140.42
  4948.5  140.63 4959.12   140.5 4991.43  130.08    5000  128.64    5011  130.35
 5043.55  139.85 5055.88  139.48 5080.54  138.75 5146.04   139.5
#Mann= 3 , 0 , 0
  4646.7     .12       0 4959.12     .04       0 5043.55     .12       0
#Block Obstruct= 2 , 0
       0    4915  140.42               0
Bank Sta=4959.12,5043.55
XS Rating Curve= 0
Exp/Cntr=.3,.1

Type RM Length L Ch R = 1 ,15012   ,112,107,110
XS GIS Cut Line= 3
    3050000.8053  13934345.80444   3050004.87579  13934304.87671
   3049934.15039  13933784.15039
#Sta/Elev= 22
 4621.37     141 4642.97   138.5 4662.97     135 4882.87     135 4906.27   138.5
 4916.77   139.9 4929.41  139.92 4935.82  139.27 4943.52  140.14 4950.78  140.52
 4959.65  140.26 4990.04  130.22    5000  129.14 5009.87  129.77 5046.62  139.89
 5058.72  139.43 5067.09  138.82 5069.47  138.36 5070.79  138.14    5074  138.91
 5086.14  138.81 5188.94   139.5
#Mann= 3 , 0 , 0
 4621.37     .12       0 4959.65     .04       0 5046.62     .12       0
#Block Obstruct= 2 , 0
       0 4916.77   139.9               0
Bank Sta=4959.65,5046.62
XS Rating Curve= 0
Exp/Cntr=.3,.1

Type RM Length L Ch R = 1 ,14905   ,94,101,100
BEGIN DESCRIPTION:
Measured
END DESCRIPTION:
XS GIS Cut Line= 4
   3050080.23834      13934347.5    3050085.4248   13934325.4248
   3050084.87793  13934039.28178   3050040.57587  13933845.57678
#Sta/Elev= 24
 4604.47     141 4627.27   138.5 4649.37     135 4881.37     135 4891.67   135.5
 4904.17   138.5 4913.35   139.9 4921.71   140.1 4928.85  139.84 4936.55  138.84
 4943.92  139.65  4952.4  140.41 4959.78  140.35 4993.39  129.61    5000  128.99
 5007.31   129.9 5044.79  139.93 5053.34  139.87 5061.52  140.04 5068.97  138.76
 5074.68  139.76  5092.1  139.18 5096.45     140 5119.25   139.5
#Mann= 3 , 0 , 0
 4604.47     .12       0 4959.78     .04       0 5044.79     .12       0
#Block Obstruct= 2 , 0
       0 4913.35   139.9               0
Bank Sta=4959.78,5044.79
XS Rating Curve= 0
Exp/Cntr=.3,.1

Type RM Length L Ch R = 1 ,14804   ,182,164,161
BEGIN DESCRIPTION:
Measured
END DESCRIPTION:
XS GIS Cut Line= 4
   3050190.35065  13934340.35156   3050170.16052  13934089.83948
   3050189.84287  13934034.16813    3050150.3462  13933862.47705
#Sta/Elev= 17
  4586.5     141  4615.2   138.5  4619.9   137.5  4636.8     135  4839.1     135
 4874.91   140.5 4898.01  141.18 4912.29  140.79 4930.93  139.63  4944.5  140.37
 4955.15  140.36 4989.78  129.99    5000   127.8 5007.86  129.56  5042.4  140.48
 5052.57  140.33 5073.86  140.26
#Mann= 3 , 0 , 0
  4586.5     .12       0 4955.15     .04       0  5042.4     .12       0
#Block Obstruct= 2 , 0
       0 4874.91   140.5               0
Bank Sta=4955.15,5042.4
XS Rating Curve= 0
Exp/Cntr=.3,.1

Type RM Length L Ch R = 1 ,14640   ,812,812,812
BEGIN DESCRIPTION:
Cross Section K140-00-00-x5b
END DESCRIPTION:
XS GIS Cut Line= 6
 3051100.528772913935737.5789224 3050688.070855413934782.8651085
       3050363.3     13934031.12      3050300.92     13933812.79
 3049711.267331213933399.5721093 3048966.040118613932877.3304014
#Sta/Elev= 30
  3025.2   141.9  3065.2  140.98  3615.2  140.45  4065.2   141.4  4155.2     140
  4165.2   140.9  4205.2   140.1  4405.2   141.5  4575.2   141.3  4884.1   140.7
  4954.8  139.48    4958  139.44    5000  127.71    5027  130.48    5056  139.57
  5074.2  138.95  5102.9  140.19  5271.2   142.9  5441.2   140.1  5461.2   141.4
  5501.2   141.8  5511.2   140.9  5651.2   142.5  5761.2     141  5791.2     142
  6201.2   141.8  6221.2   142.7  6241.2   141.8  6451.2   142.9  6741.2   141.6
#Mann= 7 ,-1 , 0
  3025.2     .12       0  4065.2     .12       0  4575.2    .045       0
  4954.8     .04       0    5056    .045       0  5102.9     .12       0
  5651.2     .06       0
Bank Sta=4954.8,5056
XS Rating Curve= 0
Exp/Cntr=.3,.1

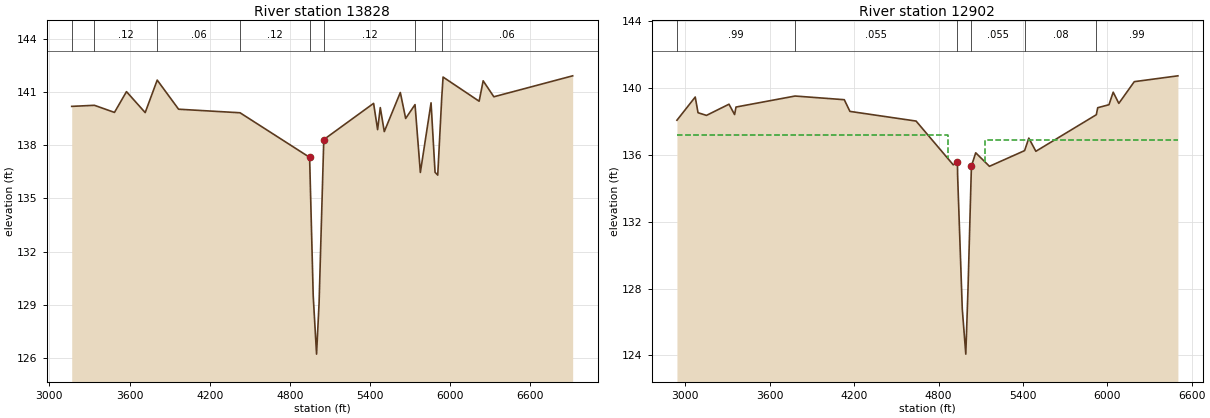
Type RM Length L Ch R = 1 ,13828   ,926,926,555
BEGIN DESCRIPTION:
Interpolated XS
END DESCRIPTION:
XS GIS Cut Line= 4
 3051678.804224513934905.7905337      3051085.94       13933660.
      3050519.18     13933040.92 3049058.371124813932585.7900208
#Sta/Elev= 30
  3167.3  140.18  3337.3  140.24  3487.3  139.84  3577.3  141.01  3717.3  139.83
  3807.3  141.66  3967.3  140.02  4427.3  139.82    4948  137.31    4975  129.51
    5000  126.23    5019  129.13  5054.1  138.31    5427  140.35    5457  138.87
    5477  140.11    5507  138.76    5627  140.96    5667   139.5    5737  140.28
    5777  136.46    5857  140.38    5887  136.47    5907  136.31    5937  140.67
    5947  141.83    6217  140.47    6247  141.62    6327  140.72    6917   141.9
#Mann= 8 ,-1 , 0
  3167.3     .06       0  3337.3     .12       0  3807.3     .06       0
  4427.3     .12       0    4948     .04       0  5054.1     .12       0
    5737    .026       0    5937     .06       0
Bank Sta=4948,5054.1
XS Rating Curve= 0
Exp/Cntr=.3,.1

Type RM Length L Ch R = 1 ,12902   ,100,100,100
BEGIN DESCRIPTION:
K140-00-00-S6_SPRING CYPRESS -US - XS 4
END DESCRIPTION:
XS GIS Cut Line= 5
      3052434.03      13934050.2      3051448.11      13932664.5
      3051227.21       13932520.       3051031.9      13932489.6
      3049631.87      13932480.2
#Sta/Elev= 30
    2940  138.08    3070  139.47    3090  138.53    3150  138.37    3310  139.04
    3350  138.42    3360  138.87    3780  139.53    4130  139.31    4170  138.61
  4640.6  138.03  4904.6  135.41  4934.6  135.56    4936  134.75    4969  126.78
    4994  124.07    5010  128.05    5034  135.33  5064.6  136.13  5162.2  135.32
  5412.2  136.26  5442.2  137.01  5492.2  136.22  5922.2  138.41  5932.2  138.83
  6012.2  139.01  6042.2  139.76  6082.2  139.09  6192.2  140.39  6502.3  140.74
#Mann= 6 ,-1 , 0
    2940     .99       0    3780    .055       0  4934.6     .04       0
    5034    .055       0  5412.2     .08       0  5922.2     .99       0
#XS Ineff= 2 , 0
       0  4864.7  137.21  5130.7       0  136.91
Permanent Ineff=
       F       F
Bank Sta=4934.6,5034
XS Rating Curve= 0
Exp/Cntr=.5,.3