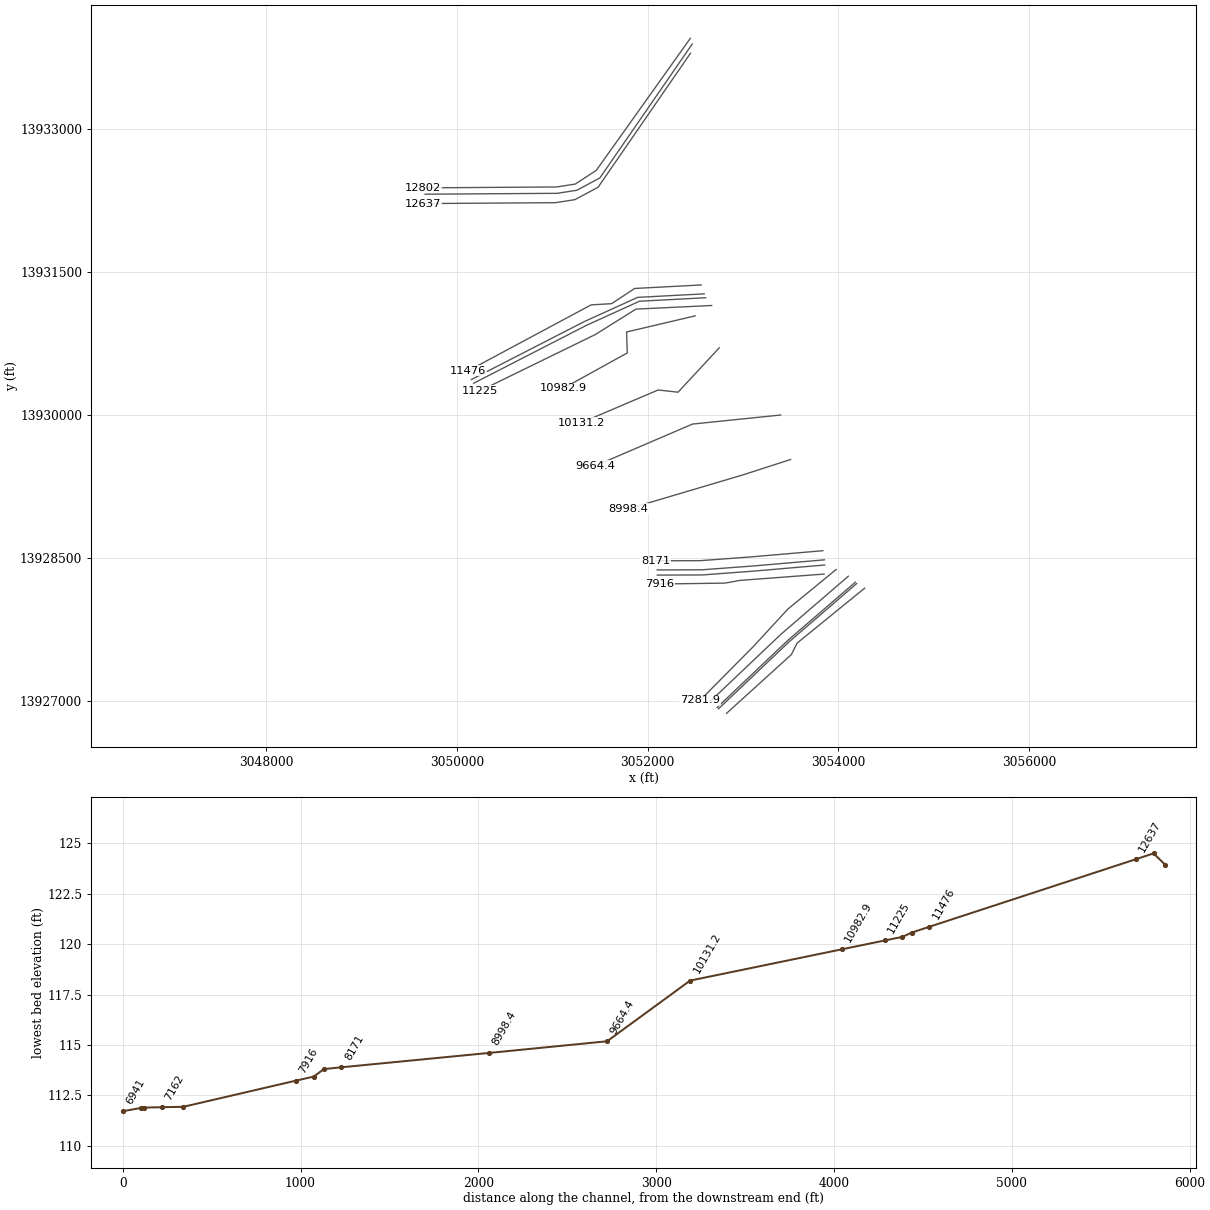
HEC-RAS study K140-00-00.prj: K140-00-00

--- K140-00-00.g01 (geometry) --- (continued)

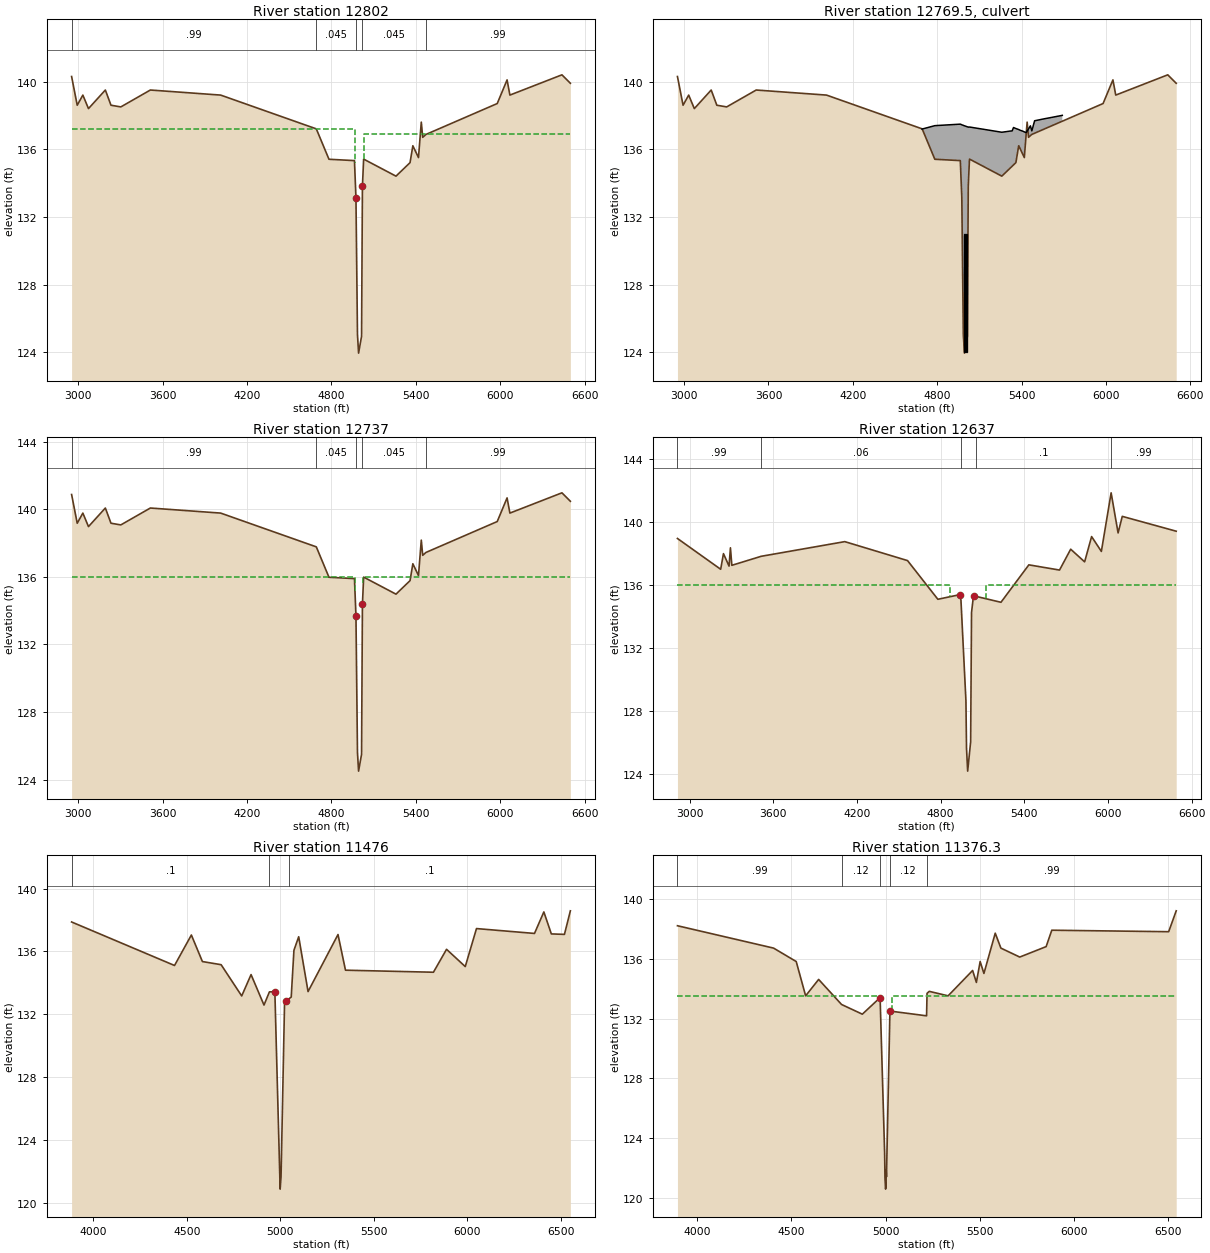
Type RM Length L Ch R = 1 ,12802   ,65,65,65
BEGIN DESCRIPTION:
K140-00-00-S6_SPRING CYPRESS -US - XS3
END DESCRIPTION:
XS GIS Cut Line= 5
 3052446.0294761 13933954.303857      3051460.09      13932568.6
       3051239.2     13932424.15      3051043.89     13932393.77
 3049643.860980513932384.3721445
#Sta/Elev= 30
  2952.8  140.32  2992.8  138.62  3032.8  139.22  3072.8  138.42  3192.8  139.52
  3232.8  138.62  3302.8  138.52  3512.8  139.52  4012.8  139.22  4692.8  137.22
  4782.8  135.42  4964.1  135.34  4974.7  133.14  4985.5  125.04  4993.4  123.94
  5014.5  124.94  5020.7  133.81  5029.3  135.43  5259.3  134.42  5359.3  135.22
  5379.3  136.22  5419.3  135.52  5439.3  137.62  5449.3  136.72  5472.5  136.89
  5979.3  138.72  6049.3  140.12  6069.3  139.22  6439.3  140.42  6499.3  139.92
#Mann= 5 ,-1 , 0
  2952.8     .99       0  4692.8    .045       0  4974.7     .04       0
  5020.7    .045       0  5472.5     .99       0
#XS Ineff= 2 , 0
       0  4964.7  137.21  5030.7       0  136.91
Permanent Ineff=
       F       F
Bank Sta=4974.7,5020.7
XS Rating Curve= 0
Exp/Cntr=.5,.3

Type RM Length L Ch R = 2 ,12769.5 ,,,
BEGIN DESCRIPTION:
SPRING-CYPRESS
Structure ID: K140-00-00-S6
END DESCRIPTION:
Bridge Culvert--1,0,-1,-1, 0
Deck Dist Width WeirC Skew NumUp NumDn MinLoCord MaxHiCord MaxSubmerge Is_Ogee
10,45,3,0, 30, 30, , , .95, 0, ,,,
  4691.5  4692.8  4782.8  4964.1  4972.8  4974.7  4985.5  4993.4  4994.9  5014.5
  5020.7  5022.7  5029.3  5259.3  5319.3  5332.5  5342.5  5359.3  5379.3  5389.3
  5409.3  5419.3  5432.5  5449.3  5462.5  5472.5  5492.5  5569.3  5589.3  5689.3
  137.21  137.21  137.41   137.5  137.47  137.46  137.43   137.4   137.4  137.34
  137.33  137.32  137.33  137.02  137.09   137.1   137.3  137.24  137.18  137.14
  137.08  137.04     137  137.22   137.4   137.1   137.7  137.83  137.86  138.02
                                                                                
                                                                                
                                                                                
  4691.5  4692.8  4782.8  4964.1  4972.8  4974.7  4985.5  4993.4  4994.9  5014.5
  5020.7  5022.7  5029.3  5259.3  5319.3  5332.5  5342.5  5359.3  5379.3  5389.3
  5409.3  5419.3  5432.5  5449.3  5462.5  5472.5  5492.5  5569.3  5589.3  5689.3
  137.81  137.81  137.41   137.5  137.47  137.46  137.43   137.4   137.4  137.34
  137.33  137.32  137.33  137.02  137.09   137.1   137.3  137.24  137.18  137.14
  137.08  137.04   137.5  137.31  137.41  137.48   137.7  138.21  137.86  138.61
                                                                                
                                                                                
                                                                                
BR Coef= 1 , 1 , 0 ,1.25, 0 ,,,.8,-1,2,0,
WSPro=,,,, 1 ,,,, 0 ,,,, 0 ,,,,-1 ,-1 ,-1 , 0 , 0 , 0 , 0 , 0
Culvert=2,7,10,45,.013,.5,1,8,3,124.01,4995.9,124.58,4995.9,Culvert #1  , 0 ,10
Culvert Bottom n=.013
Culvert=2,7,10,45,.013,.5,1,8,3,124.01,5007.1,124.58,5007.1,Culvert #2  , 0 ,10
Culvert Bottom n=.013
BC Design=,, 0 ,, 0 ,,,,,,
BC HTab HWMax=140.42

Type RM Length L Ch R = 1 ,12737   ,98.11,100,115.38
BEGIN DESCRIPTION:
K140-00-00-S6_SPRING CYPRESS -DS - XS2
END DESCRIPTION:
XS GIS Cut Line= 5
 3052466.401214413933895.2124861      3051497.61       13932489.
      3051254.71     13932358.89      3051050.17     13932327.07
 3049663.468087613932317.7617674
#Sta/Elev= 30
  2952.8  140.88  2992.8  139.18  3032.8  139.78  3072.8  138.98  3192.8  140.08
  3232.8  139.18  3302.8  139.08  3512.8  140.08  4012.8  139.78  4692.8  137.78
  4782.8  135.98  4964.1   135.9  4974.7   133.7  4985.5   125.6  4993.4   124.5
  5014.5   125.5  5020.7  134.37  5029.3  135.99  5259.3  134.98  5359.3  135.78
  5379.3  136.78  5419.3  136.08  5439.3  138.18  5449.3  137.28  5472.5  137.45
  5979.3  139.28  6049.3  140.68  6069.3  139.78  6439.3  140.98  6499.3  140.48
#Mann= 5 ,-1 , 0
  2952.8     .99       0  4692.8    .045       0  4974.7    .055       0
  5020.7    .045       0  5472.5     .99       0
#XS Ineff= 2 , 0
       0 4968.03     136 5027.37       0     136
Permanent Ineff=
       F       F
Bank Sta=4974.7,5020.7
XS Rating Curve= 0
Exp/Cntr=.5,.3

Type RM Length L Ch R = 1 ,12637   ,1137.07,1161,1324.58
BEGIN DESCRIPTION:
K140-00-00-S6_SPRING CYPRESS -DS - XS 1
END DESCRIPTION:
XS GIS Cut Line= 5
      3052447.22      13933796.9      3051478.43      13932390.7
      3051235.53      13932260.5      3051030.99      13932228.7
      3049644.29      13932219.4
#Sta/Elev= 30
  2912.6  138.94  3222.6  136.99  3242.6  137.98  3282.6  137.19  3292.6  138.35
  3302.6  137.24  3512.6  137.81  4112.6  138.74  4562.6  137.54  4780.2  135.09
  4935.8  135.38  4945.8  135.03 4981.46  128.66 4985.65  125.65 4993.87  124.21
 5015.27  126.07 5021.56  134.25  5035.8  135.32  5055.8  135.27  5232.7   134.9
  5432.7  137.27  5652.7  136.94  5732.7  138.26  5832.7  137.46  5882.7  139.06
  5952.7  138.12  6022.7  141.83  6072.7  139.29  6102.7  140.34  6489.5   139.4
#Mann= 5 ,-1 , 0
  2912.6     .99       0  3512.6     .06       0  4945.8     .05       0
  5055.8      .1       0  6022.7     .99       0
#XS Ineff= 2 , 0
       0 4868.03     136 5127.37       0     136
Permanent Ineff=
       F       F
Bank Sta=4935.8,5035.8
XS Rating Curve= 0
Exp/Cntr=.3,.1

Type RM Length L Ch R = 1 ,11476   ,99.7,99.7,99.7
BEGIN DESCRIPTION:
K140-00-00-S5_COSSEY -US - XS4
END DESCRIPTION:
XS GIS Cut Line= 5
      3052559.81      13931364.8      3051861.73       13931328.
      3051620.65      13931168.5      3051405.53      13931155.7
      3050117.44      13930464.8
#Sta/Elev= 30
  3884.9  137.87  4434.9   135.1  4524.9  137.04  4583.9  135.35  4683.9  135.15
  4793.9  133.16  4843.9  134.52    4913  132.58 4942.02  133.42 4971.09  133.43
 4999.33  120.86 5004.09  121.64 5022.74  132.65 5031.55  132.84  5045.6  132.97
 5058.47  133.09    5073  136.07  5098.5  136.93  5148.5  133.44  5308.5  137.07
  5348.5   134.8  5818.5  134.67  5888.5  136.13  5988.5  135.03  6048.5  137.45
  6358.5  137.14  6408.5  138.51  6448.5  137.11  6518.5  137.08  6550.2  138.58
#Mann= 3 ,-1 , 0
  3884.9      .1       0 4942.02     .06       0  5045.6      .1       0
Bank Sta=4971.09,5031.55
XS Rating Curve= 0
Exp/Cntr=.5,.3

Type RM Length L Ch R = 1 ,11376.3 ,51,51,51
BEGIN DESCRIPTION:
K140-00-00-S5_COSSEY -US - XS3
END DESCRIPTION:
XS GIS Cut Line= 4
 3052590.975343213931271.3293406       3051892.9     13931234.57
      3051331.66     13930979.19 3050148.610721513930371.3143968
#Sta/Elev= 30
  3895.8  138.23  4405.8  136.73  4525.8  135.83  4575.8  133.53  4644.8  134.63
  4766.3  132.95  4876.5   132.3  4970.8  133.41  4994.9  122.95  4996.6  121.33
  4999.8  120.57  5002.5  120.81    5003  121.83  5004.5  121.39  5022.9  132.51
  5217.3  132.19  5219.8   133.7  5231.5  133.83  5331.5  133.53  5461.5  135.23
  5481.5  134.43  5501.5  135.83  5521.5  135.03  5581.5  137.73  5611.5  136.73
  5711.5  136.13  5851.5  136.83  5881.5  137.93  6501.5  137.83  6541.5  139.23
#Mann= 5 ,-1 , 0
  3895.8     .99       0  4766.3     .12       0  4970.8     .06       0
  5022.9     .12       0  5217.3     .99       0
#XS Ineff= 2 , 0
       0  4960.8   133.5  5032.9       0   133.5
Permanent Ineff=
       F       F
Bank Sta=4970.8,5022.9
XS Rating Curve= 0
Exp/Cntr=.5,.3

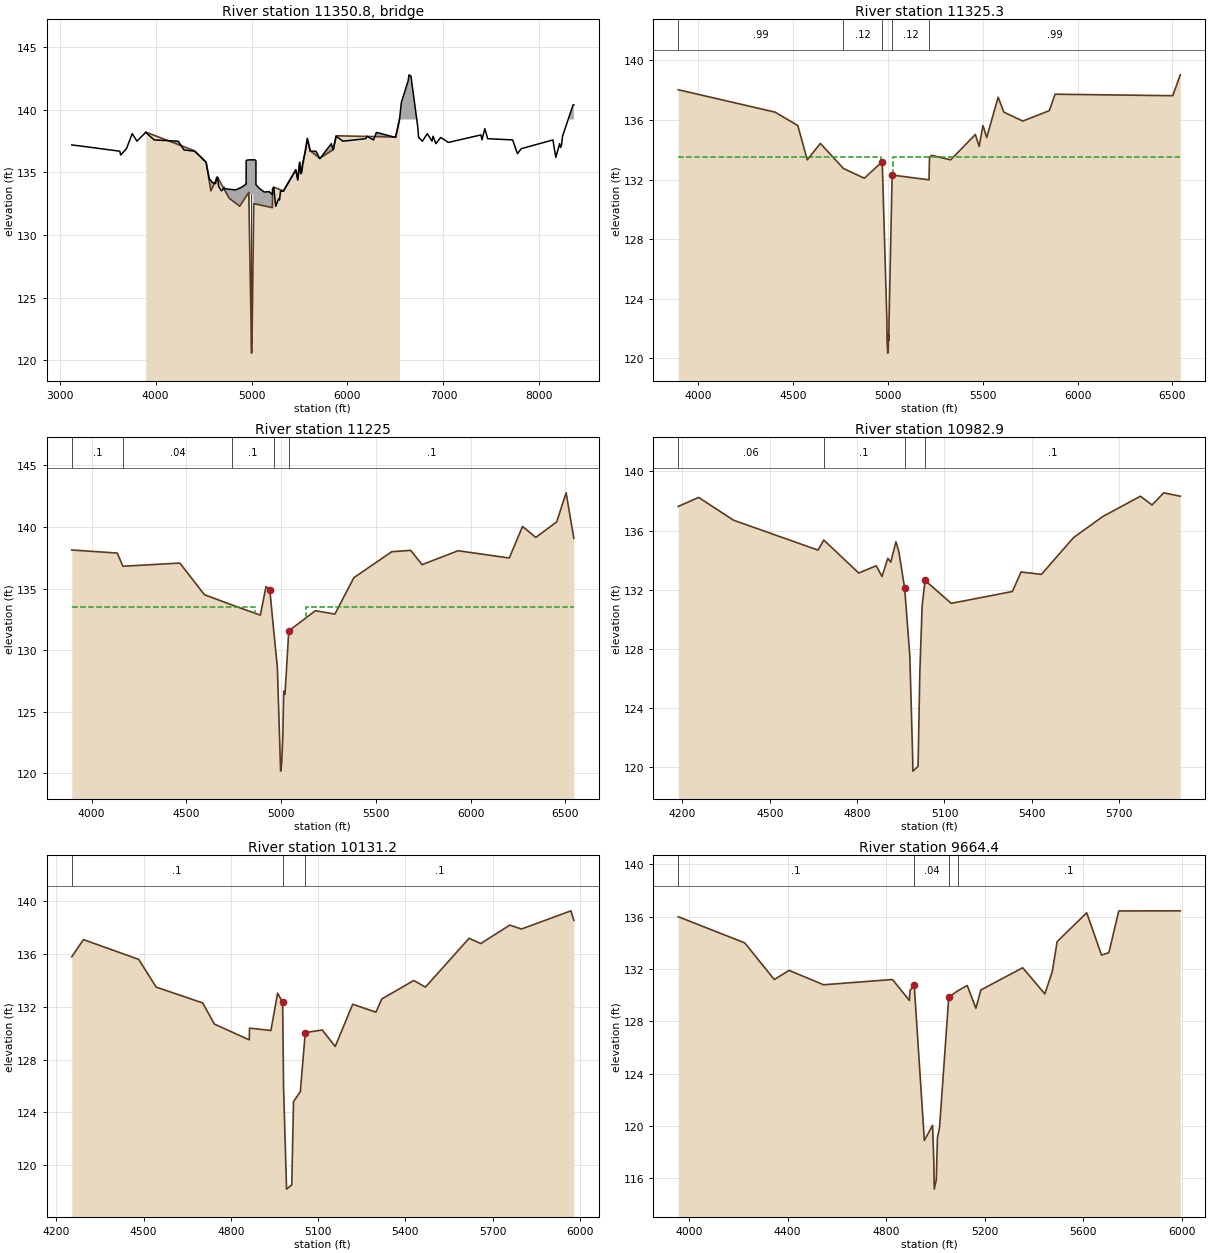
Type RM Length L Ch R = 3 ,11350.8 ,,,
BEGIN DESCRIPTION:
COSSEY RD
Structure ID: K140-00-00-S5
END DESCRIPTION:
Bridge Culvert--1,0,-1,-1, 0
Deck Dist Width WeirC Skew NumUp NumDn MinLoCord MaxHiCord MaxSubmerge Is_Ogee
10,31,2.6,0, 137, 137, , , .95, 0, ,,,
  3125.8  3240.1  3625.8  3635.8  3695.8  3755.8  3805.8  3895.8  3985.8  4235.8
  4295.8  4405.8  4470.1  4525.8  4560.1  4575.8  4594.8  4624.8  4634.8  4644.8
  4650.1  4657.5  4684.8  4694.8  4714.8  4717.5  4734.8  4764.8  4766.3  4817.6
  4834.7  4876.5    4891  4925.7  4940.9 4943.39  4943.5 4943.61 4968.69  4968.8
 4968.91 4970.09  4970.2 4970.31  4970.8 4981.21  4981.3  4981.4  4982.5  4994.9
  4996.6  4999.5  4999.6  4999.8  5000.2  5000.5  5002.5    5003  5004.5  5014.1
  5018.6 5018.69  5018.8  5022.9 5035.29  5035.4 5035.51 5043.79  5043.9 5044.01
 5045.59  5045.7 5045.81  5058.7  5083.2  5110.3    5132  5163.9  5183.5  5217.3
  5219.8  5231.5  5235.4  5251.5  5281.5  5291.5  5301.5  5331.5  5461.5  5481.5
  5501.5  5511.5  5521.5  5531.5  5561.5  5581.5  5611.5  5671.5  5711.5  5831.5
  5851.5  5881.5  5951.5  6191.5  6201.5  6271.5  6301.5  6501.5  6541.5  6561.5
  6631.5  6641.5  6661.5  6731.5  6741.5  6781.5  6831.5  6881.5  6891.5  6921.5
  6971.5  7051.5  7391.5  7401.5  7431.5  7461.5  7721.5  7771.5  7811.5  8141.5
  8171.5  8211.5  8221.5  8231.5  8241.5  8351.5  8359.5
   137.2  137.09   136.7   136.4   136.9   138.1   137.5   138.2   137.6   137.5
   136.8   136.7  136.23  135.81   134.5  134.36  134.19  134.11  134.61  134.61
  134.31  133.88  133.54  133.59  133.81   133.7  133.69  133.66  133.66  133.62
  133.61  133.75   133.8  133.98  134.06  134.06  135.96  135.96  136.01  136.01
  136.01  136.01  136.01  136.01  136.01  136.01  136.01  136.01  136.01  136.01
  136.01  136.01  136.01  136.01  136.01  136.01  136.01  136.01  136.01  136.01
  136.01  136.01  136.01  136.01  136.01  136.01  136.01  135.93  135.93  135.93
  135.92  135.92  134.02  133.92  133.72  133.56  133.44  133.46  133.47  133.23
  133.68  133.81  133.52   132.3   132.9   132.8   133.5   133.5   135.2   134.4
   135.8   134.9     135   135.7   136.7   137.7   136.7   136.7   136.1   137.3
   136.8   137.9   137.5   137.7   137.9   137.6   138.2   137.8   139.2   140.6
   142.3   142.8   142.7   138.7   137.8   137.5   138.1   137.5   137.9   137.3
   137.8   137.4     138   137.6   138.5   137.7   137.6   136.5   136.9   137.6
   136.2   137.3     137   137.2   137.9   140.4   140.4
                                                                                
                                                                                
                                                                                
                                                                                
                                          129.08  133.26  133.26  133.26  133.26
  133.26  133.26  133.26  133.26  133.26  133.26  133.26  133.26  133.26  133.26
  133.26  133.26  130.26
                                                                                
                                                                                
                                                                                
                                                                                
                                                                                
                                                                                
                                                        
  3125.8  3240.1  3625.8  3635.8  3695.8  3755.8  3805.8  3895.8  3985.8  4235.8
  4295.8  4405.8  4470.1  4525.8  4560.1  4575.8  4594.8  4624.8  4634.8  4644.8
  4650.1  4657.5  4684.8  4694.8  4714.8  4717.5  4734.8  4764.8  4766.3  4817.6
  4834.7  4876.5    4891  4925.7  4940.9 4943.39  4943.5 4943.61 4968.69  4968.8
 4968.91 4970.09  4970.2 4970.31  4970.8 4981.21  4981.3  4981.4  4982.5  4994.9
  4996.6  4999.5  4999.6  4999.8  5000.2  5000.5  5002.5    5003  5004.5  5014.1
  5018.6 5018.69  5018.8  5022.9 5035.29  5035.4 5035.51 5043.79  5043.9 5044.01
 5045.59  5045.7 5045.81  5058.7  5083.2  5110.3    5132  5163.9  5183.5  5217.3
  5219.8  5231.5  5235.4  5251.5  5281.5  5291.5  5301.5  5331.5  5461.5  5481.5
  5501.5  5511.5  5521.5  5531.5  5561.5  5581.5  5611.5  5671.5  5711.5  5831.5
  5851.5  5881.5  5951.5  6191.5  6201.5  6271.5  6301.5  6501.5  6541.5  6561.5
  6631.5  6641.5  6661.5  6731.5  6741.5  6781.5  6831.5  6881.5  6891.5  6921.5
  6971.5  7051.5  7391.5  7401.5  7431.5  7461.5  7721.5  7771.5  7811.5  8141.5
  8171.5  8211.5  8221.5  8231.5  8241.5  8351.5  8359.5
   137.2  137.09   136.7   136.4   136.9   138.1   137.5   138.2   137.6   137.5
   136.8   136.7  136.23  135.81   134.5  134.36  134.19  134.11  134.61  134.61
  134.31  133.88  133.54  133.59  133.81   133.7  133.69  133.66  133.66  133.62
  133.61  133.75   133.8  133.98  134.06  134.06  135.96  135.96  136.01  136.01
  136.01  136.01  136.01  136.01  136.01  136.01  136.01  136.01  136.01  136.01
  136.01  136.01  136.01  136.01  136.01  136.01  136.01  136.01  136.01  136.01
  136.01  136.01  136.01  136.01  136.01  136.01  136.01  135.93  135.93  135.93
  135.92  135.92  134.02  133.92  133.72  133.56  133.44  133.46  133.47  133.23
  133.68  133.81  133.52   132.3   132.9   132.8   133.5   133.5   135.2   134.4
   135.8   134.9     135   135.7   136.7   137.7   136.7   136.7   136.1   137.3
   136.8   137.9   137.5   137.7   137.9   137.6   138.2   137.8   139.2   140.6
   142.3   142.8   142.7   138.7   137.8   137.5   138.1   137.5   137.9   137.3
   137.8   137.4     138   137.6   138.5   137.7   137.6   136.5   136.9   137.6
   136.2   137.3     137   137.2   137.9   140.4   140.4
                                                                                
                                                                                
                                                                                
                                                                                
                                          128.96  133.14  133.14  133.14  133.14
  133.14  133.14  133.14  133.14  133.14  133.14  133.14  133.14  133.14  133.14
  133.14  133.14  130.14
                                                                                
                                                                                
                                                                                
                                                                                
                                                                                
                                                                                
                                                        
Pier Skew, UpSta & Num, DnSta & Num=  ,4997.1, 2 ,4997.1, 2 , 0 , 0 , 0 ,,
     1.5     1.5
  119.98  134.26
     1.5     1.5
  119.86  134.14
BR Coef= 1 , 1 , 1 ,.9, 0 ,,,.8,0,1.2,0,
WSPro=,,,, 1 ,,,, 0 ,,,, 0 ,,,,-1 ,-1 ,-1 , 0 , 0 , 0 , 0 , 0
BC Design=,, 0 ,, 0 ,,,,,,
BC HTab HWMax=139.23

Type RM Length L Ch R = 1 ,11325.3 ,67.37,100.3,120.98
BEGIN DESCRIPTION:
K140-00-00-S5_COSSEY -DS - XS2
END DESCRIPTION:
XS GIS Cut Line= 4
 3052607.595316913931230.7298396       3051913.3     13931194.17
      3051355.94     13930940.55    3050173.320513930332.8948277
#Sta/Elev= 30
  3895.8  138.02  4405.8  136.52  4525.8  135.62  4575.8  133.32  4644.8  134.42
  4766.3  132.74  4876.5  132.09  4970.8   133.2  4994.9  122.74  4996.6  121.12
  4999.8  120.36  5002.5   120.6    5003  121.62  5004.5  121.18  5022.9   132.3
  5217.3  131.98  5219.8  133.49  5231.5  133.62  5331.5  133.32  5461.5  135.02
  5481.5  134.22  5501.5  135.62  5521.5  134.82  5581.5  137.52  5611.5  136.52
  5711.5  135.92  5851.5  136.62  5881.5  137.72  6501.5  137.62  6541.5  139.02
#Mann= 5 ,-1 , 0
  3895.8     .99       0  4766.3     .12       0  4970.8     .06       0
  5022.9     .12       0  5217.3     .99       0
#XS Ineff= 2 , 0
       0 4964.13   133.5 5029.57       0   133.5
Permanent Ineff=
       F       F
Bank Sta=4970.8,5022.9
XS Rating Curve= 0
Exp/Cntr=.5,.3

Type RM Length L Ch R = 1 ,11225   ,162.63,242.1,292.02
BEGIN DESCRIPTION:
K140-00-00-S5_COSSEY -DS - XS 1
END DESCRIPTION:
XS GIS Cut Line= 4
      3052669.93      13931149.2      3051875.95      13931111.3
      3051449.33      13930844.2      3050235.66      13930251.3
#Sta/Elev= 30
  3895.5  138.13  4135.5  137.88  4165.5  136.81  4465.5  137.07  4595.5   134.5
  4740.4  133.67  4890.4  132.84  4920.4  135.16  4940.4  134.92  4960.4  131.67
 4980.23   128.6 4997.37  120.18 5003.19  120.83 5009.18  123.09 5013.69  126.67
  5020.4  126.41  5040.4  131.56  5180.4   133.2  5283.7  132.93  5383.7  135.88
  5583.7  137.99  5683.7   138.1  5743.7  136.94  5933.7  138.07  6203.7  137.48
  6273.7  140.04  6343.7  139.15  6453.7  140.41  6503.7  142.77  6544.4  139.08
#Mann= 5 ,-1 , 0
  3895.5      .1       0  4165.5     .04       0  4740.4      .1       0
  4960.4     .06       0  5040.4      .1       0
#XS Ineff= 2 , 0
       0 4864.13   133.5 5129.57       0   133.5
Permanent Ineff=
       F       F
Bank Sta=4940.4,5040.4
XS Rating Curve= 0
Exp/Cntr=.3,.1

Type RM Length L Ch R = 1 ,10982.9 ,867.9,851.7,641.2
BEGIN DESCRIPTION:
Interpolated XS
END DESCRIPTION:
XS GIS Cut Line= 4
       3052495.5       13931040.      3051777.28      13930871.1
      3051784.66     13930651.26      3051113.67     13930279.82
#Sta/Elev= 30
  4185.5  137.63  4255.5  138.24  4375.5   136.7  4665.5  134.68  4685.5  135.36
  4805.5  133.13  4865.5  133.62  4885.5   132.9  4905.5  134.13  4915.5  133.86
  4933.4  135.24  4943.4  134.57  4963.4   132.1  4981.2  127.49  4991.1  120.49
  4991.5  119.74  5009.4  120.06  5015.4  126.37  5023.4  130.91  5033.4  132.63
  5123.4  131.08  5333.3  131.88  5363.3   133.2  5433.3  133.04  5543.3  135.52
  5643.3  136.94  5773.3  138.32  5813.3  137.73  5853.3  138.55  5910.3  138.32
#Mann= 4 ,-1 , 0
  4185.5     .06       0  4685.5      .1       0  4963.4     .08       0
  5033.4      .1       0
Bank Sta=4963.4,5033.4
XS Rating Curve= 0
Exp/Cntr=.3,.1

Type RM Length L Ch R = 1 ,10131.2 ,466.8,466.8,466.8
BEGIN DESCRIPTION:
Cross Section K140-00-00-X5
END DESCRIPTION:
XS GIS Cut Line= 4
      3052749.79     13930705.02       3052317.5     13930238.88
      3052109.16     13930262.31 3051299.548799513929917.5342269
#Sta/Elev= 30
  4253.4   135.8  4293.4   137.1  4483.4   135.6  4543.4   133.5  4703.4   132.3
  4743.4   130.7  4863.4   129.5  4864.3  130.39  4937.7  130.21  4960.8  133.04
    4978  132.35  4981.2  125.94  4991.5  118.19  5009.4  118.51  5015.4  124.82
  5038.9  125.58  5055.8  130.05  5114.3  130.25  5158.8     129  5218.8   132.2
  5298.8   131.6  5318.8   132.6  5428.8     134  5468.8   133.5  5618.8   137.2
  5658.8   136.8  5758.8   138.2  5798.8   137.9  5968.8  139.28  5978.8  138.56
#Mann= 3 ,-1 , 0
  4253.4      .1       0    4978     .08       0  5055.8      .1       0
Bank Sta=4978,5055.8
XS Rating Curve= 0
Exp/Cntr=.3,.1

Type RM Length L Ch R = 1 ,9664.4  ,666,666,666
BEGIN DESCRIPTION:
Cross Section K140-00-00-X4; trib coming in on left 11/13/2 VRR
END DESCRIPTION:
XS GIS Cut Line= 3
      3053393.02     13929999.29      3052469.33     13929904.37
 3051449.451070613929466.2093904
#Sta/Elev= 30
  3956.3     136  4226.3     134  4346.3   131.2  4406.3   131.9  4546.3   130.8
  4826.3   131.2  4894.9   129.6  4897.4  130.36  4914.4  130.79  4955.6   118.9
    4989  120.06  4994.2  117.23  4995.9  115.18  5004.1  115.89  5008.7  119.09
  5017.3  119.89  5054.7  129.85  5092.4  130.35  5129.8  130.74  5164.9     129
  5184.9   130.4  5354.9   132.1  5444.9   130.1  5474.9   131.8  5494.9   134.1
  5614.9   136.3  5674.9  133.07  5704.9  133.25  5744.9  136.44  5994.9  136.45
#Mann= 4 ,-1 , 0
  3956.3      .1       0  4914.4     .04       0  5054.7    .045       0
  5092.4      .1       0
Bank Sta=4914.4,5054.7
XS Rating Curve= 0
Exp/Cntr=.3,.1

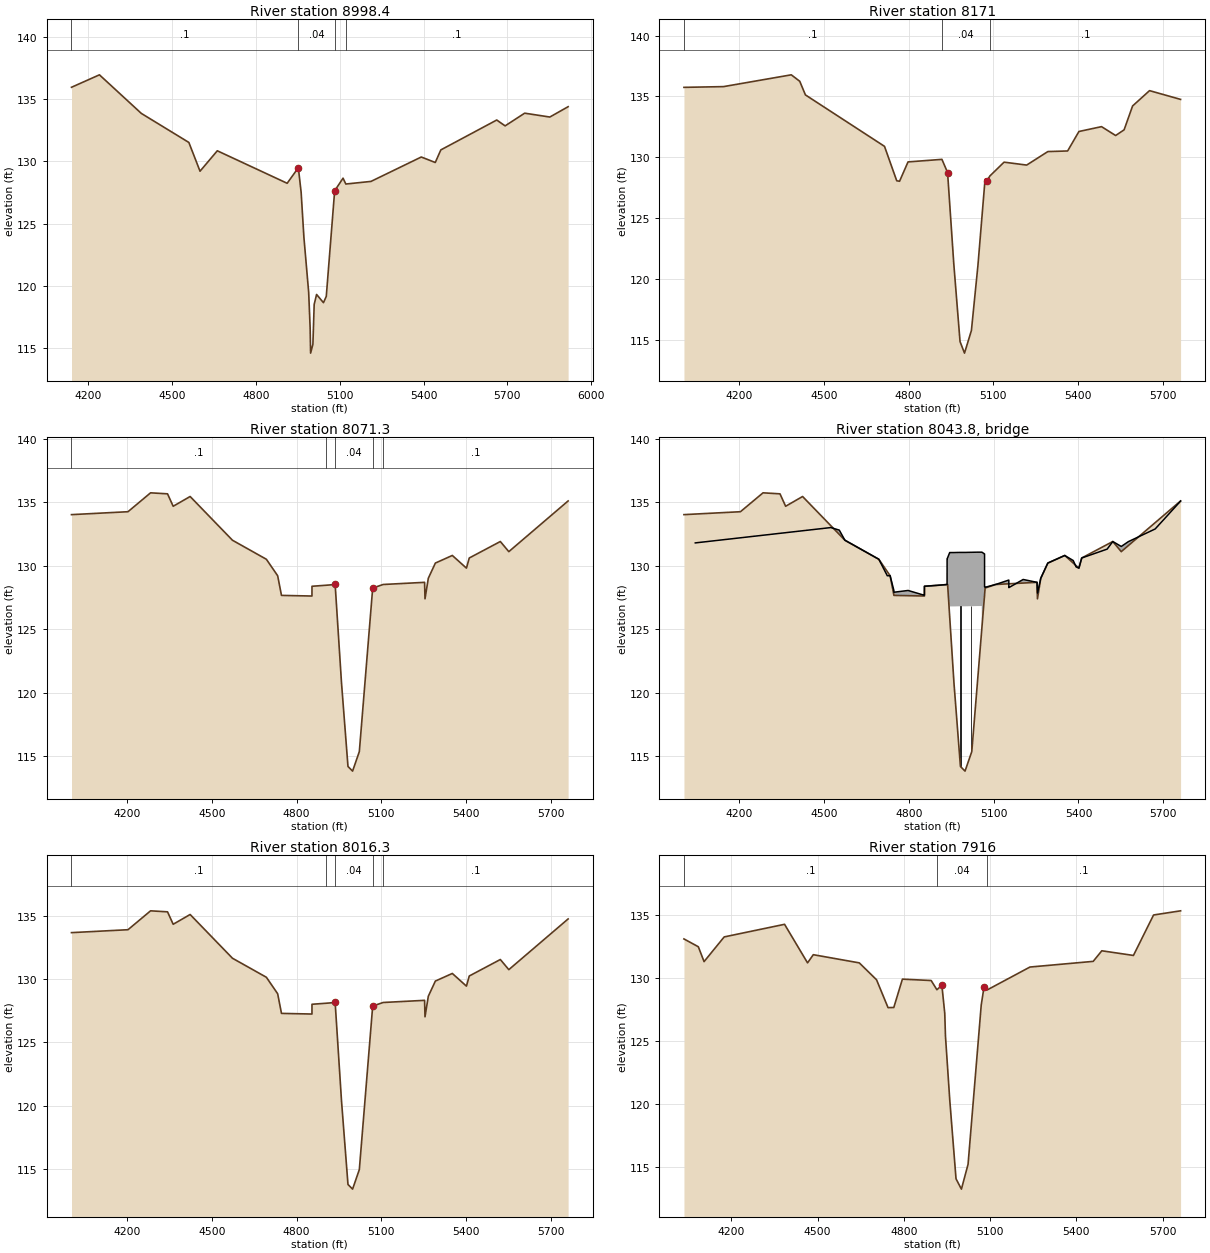
Type RM Length L Ch R = 1 ,8998.4  ,827.4,827.4,827.4
BEGIN DESCRIPTION:
Interpolated XS
END DESCRIPTION:
XS GIS Cut Line= 3
       3053497.1       13929532.      3053000.75     13929371.52
      3051797.16     13929014.37
#Sta/Elev= 30
  4140.2  135.95  4240.2  136.95  4390.2  133.85  4560.2  131.52  4600.2  129.21
    4662  130.85    4912  128.24    4952  129.49    4962  127.52    4972  123.88
    4989  119.48  4994.2  116.65  4995.9   114.6  5004.1  115.31  5008.7  118.51
  5017.3  119.31    5042  118.65    5052  119.16    5082  127.64    5112  128.65
    5122  128.18    5212  128.39    5392  130.35    5442  129.91    5462  130.92
    5662  133.32    5692  132.85    5762  133.87    5852  133.56  5917.5  134.39
#Mann= 4 ,-1 , 0
  4140.2      .1       0    4952     .04       0    5082    .045       0
    5122      .1       0
Bank Sta=4952,5082
XS Rating Curve= 0
Exp/Cntr=.3,.1

Type RM Length L Ch R = 1 ,8171    ,99.7,99.7,99.7
BEGIN DESCRIPTION:
K140-00-00-S04_RODGERS RD -US - XS 4
END DESCRIPTION:
XS GIS Cut Line= 4
      3053836.03      13928574.7      3053095.49      13928510.7
      3052551.95      13928470.2      3052082.05      13928468.7
#Sta/Elev= 30
    4005  135.74    4145   135.8    4385  136.77    4415  136.24    4435  135.12
    4715  130.89  4758.3  128.06  4768.3  128.02  4798.3  129.61  4918.3  129.82
  4938.3  128.74 4960.24  121.25 4982.43  114.84 4998.22  113.89 5022.66  115.75
 5045.66  121.07 5071.02  128.18  5078.3  128.08  5088.3  128.46  5138.3  129.59
  5218.3  129.35  5293.3  130.46  5363.3  130.51  5403.3  132.11  5483.3  132.51
  5533.3  131.78  5563.3  132.25  5593.3  134.21  5653.3  135.47  5763.2  134.75
#Mann= 3 ,-1 , 0
    4005      .1       0  4918.3     .04       0  5088.3      .1       0
Bank Sta=4938.3,5078.3
XS Rating Curve= 0
Exp/Cntr=.5,.3

Type RM Length L Ch R = 1 ,8071.3  ,55,55,55
BEGIN DESCRIPTION:
K140-00-00-S04_RODGERS RD -US - XS3
END DESCRIPTION:
XS GIS Cut Line= 4
 3053852.8120021 13928478.798078      3053112.27     13928414.83
      3052568.74      13928374.3 3052098.833178913928372.8441387
#Sta/Elev= 30
  4003.4  134.03  4203.4  134.26  4283.4  135.75  4343.4  135.67  4363.4  134.69
  4423.4  135.46  4573.3  132.01  4693.3  130.51  4733.3  129.21  4746.8  127.66
  4854.7  127.61  4854.8  128.38  4904.3  128.46  4936.8  128.52  4959.3  120.76
  4982.2  114.17  4998.5   113.8  5022.4  115.34  5069.7  128.24  5106.7  128.52
  5253.4  128.69  5254.9  127.39  5266.6  129.01  5291.6  130.21  5351.6  130.81
  5401.6  129.81  5411.6  130.61  5521.6  131.91  5551.6  131.11  5761.6  135.11
#Mann= 5 ,-1 , 0
  4003.4      .1       0  4904.3    .045       0  4936.8     .04       0
  5069.7    .045       0  5106.7      .1       0
#XS Ineff= 2 , 0
       0  4926.8  127.68  5079.7       0  127.84
Permanent Ineff=
       F       F
Bank Sta=4936.8,5069.7
XS Rating Curve= 0
Exp/Cntr=.5,.3

Type RM Length L Ch R = 3 ,8043.8  ,,,
BEGIN DESCRIPTION:
RODGERS ROAD
Structure ID: K140-00-00-S04
END DESCRIPTION:
Bridge Culvert--1,0,-1,-1, 0
Deck Dist Width WeirC Skew NumUp NumDn MinLoCord MaxHiCord MaxSubmerge Is_Ogee
10,35,2.6,0, 72, 72, , , .95, 0, ,,,
  4043.5  4523.3  4553.3  4573.3  4693.3  4703.5  4719.6  4723.3  4733.3  4746.5
  4746.8  4797.1  4799.7  4799.9  4852.8  4854.7  4854.8  4904.3 4934.89    4935
 4935.11  4936.8 4944.19  4944.3 4944.41 4944.51  4944.6  4944.7  4959.3  4978.7
  4980.3  4982.2  4998.5  5020.5  5021.2  5022.4  5043.9  5057.6 5057.69  5057.8
 5057.89    5058  5058.1 5058.21 5067.49  5067.6 5067.71  5069.7  5106.7  5153.5
  5153.6  5156.5  5204.5  5205.8  5253.4  5254.9  5266.6  5287.4  5291.6  5351.6
  5357.4  5381.6  5391.6  5401.6  5411.6  5501.6  5521.6  5551.6  5576.7  5671.6
    5718  5761.6
   131.8  133.01  132.81  132.01  130.51  130.07  129.37  129.21  129.21  128.06
  127.91  128.05  128.03  128.03  127.68  127.69  128.38  128.46  128.52  130.54
  130.54  130.63  131.04  131.04  131.04  131.04  131.04  131.04  131.04  131.05
  131.05  131.05  131.05  131.06  131.06  131.06  131.07  131.07  131.07  131.07
  131.07  131.07  131.07  131.07  130.93  130.93  128.33   128.3  128.52  128.87
  128.27  128.31  128.92  128.91  128.69  127.84  129.01  130.01  130.21  130.81
  130.73  130.41  129.91  129.81  130.61  131.31  131.91  131.52   131.9   132.9
  134.03   135.1
                                                                                
                                                                                
                                          125.85  126.79  126.79  126.79   126.8
   126.8   126.8   126.8  126.81  126.81  126.81  126.82  126.82  126.82   124.9
                                                                                
                                                                                
                                                                                
                
  4043.5  4523.3  4553.3  4573.3  4693.3  4703.5  4719.6  4723.3  4733.3  4746.5
  4746.8  4797.1  4799.7  4799.9  4852.8  4854.7  4854.8  4904.3 4934.89    4935
 4935.11  4936.8 4944.19  4944.3 4944.41 4944.51  4944.6  4944.7  4959.3  4978.7
  4980.3  4982.2  4998.5  5020.5  5021.2  5022.4  5043.9  5057.6 5057.69  5057.8
 5057.89    5058  5058.1 5058.21 5067.49  5067.6 5067.71  5069.7  5106.7  5153.5
  5153.6  5156.5  5204.5  5205.8  5253.4  5254.9  5266.6  5287.4  5291.6  5351.6
  5357.4  5381.6  5391.6  5401.6  5411.6  5501.6  5521.6  5551.6  5576.7  5671.6
    5718  5761.6
   131.8  133.01  132.81  132.01  130.51  130.07  129.37  129.21  129.21  128.06
  127.91  128.05  128.03  128.03  127.68  127.69  128.38  128.46  128.52  130.54
  130.54  130.63  131.04  131.04  131.04  131.04  131.04  131.04  131.04  131.05
  131.05  131.05  131.05  131.06  131.06  131.06  131.07  131.07  131.07  131.07
  131.07  131.07  131.07  131.07  130.93  130.93  128.33   128.3  128.52  128.87
  128.27  128.31  128.92  128.91  128.69  127.84  129.01  130.01  130.21  130.81
  130.73  130.41  129.91  129.81  130.61  131.31  131.91  131.52   131.9   132.9
  134.03   135.1
                                                                                
                                                                                
                                          125.51  126.45  126.45  126.45  126.46
  126.46  126.46  126.46  126.47  126.47  126.47  126.48  126.48  126.48  124.56
                                                                                
                                                                                
                                                                                
                
Pier Skew, UpSta & Num, DnSta & Num=  ,4982.2, 2 ,4982.2, 2 , 0 , 0 , 0 ,,
     1.4     1.4
  113.14   127.8
     1.4     1.4
   112.8  127.46
Pier Skew, UpSta & Num, DnSta & Num=  ,5020.5, 2 ,5020.5, 2 , 0 , 0 , 0 ,,
     1.4     1.4
  114.11  127.81
     1.4     1.4
  113.77  127.47
BR Coef= 1 , 1 , 1 ,1.25, 0 ,,,.8,0,2,0,
WSPro=,,,, 1 ,,,, 0 ,,,, 0 ,,,,-1 ,-1 ,-1 , 0 , 0 , 0 , 0 , 0
BC Design=,, 0 ,, 0 ,,,,,,
BC HTab HWMax=135.75

Type RM Length L Ch R = 1 ,8016.3  ,94.51,100.3,106.8
BEGIN DESCRIPTION:
K140-00-00-S04_RODGERS RD -DS - XS2
END DESCRIPTION:
XS GIS Cut Line= 4
 3053855.571813713928424.6202592      3053114.91     13928360.65
      3052570.55     13928320.06  3052099.93316113928318.5999339
#Sta/Elev= 30
  4003.4  133.66  4203.4  133.89  4283.4  135.38  4343.4   135.3  4363.4  134.32
  4423.4  135.09  4573.3  131.64  4693.3  130.14  4733.3  128.84  4746.8  127.29
  4854.7  127.24  4854.8  128.01  4904.3  128.09  4936.8  128.15  4959.3  120.39
  4982.2   113.8  4998.5  113.43  5022.4  114.97  5069.7  127.87  5106.7  128.15
  5253.4  128.32  5254.9  127.02  5266.6  128.64  5291.6  129.84  5351.6  130.44
  5401.6  129.44  5411.6  130.24  5521.6  131.54  5551.6  130.74  5761.6  134.74
#Mann= 5 ,-1 , 0
  4003.4      .1       0  4904.3    .045       0  4936.8     .04       0
  5069.7    .045       0  5106.7      .1       0
#XS Ineff= 2 , 0
       0 4930.13  127.31 5076.37       0  127.47
Permanent Ineff=
       F       F
Bank Sta=4936.8,5069.7
XS Rating Curve= 0
Exp/Cntr=.5,.3

Type RM Length L Ch R = 1 ,7916    ,597.49,634.1,675.2
BEGIN DESCRIPTION:
K140-00-00-S04_RODGERS RD -DS - XS1
END DESCRIPTION:
XS GIS Cut Line= 4
      3053848.84      13928329.3      3052964.05      13928262.6
      3052810.17      13928234.4      3052126.31       13928225.
#Sta/Elev= 30
  4034.9  133.08  4084.9  132.46  4104.9  131.28  4174.9  133.24  4384.9  134.24
  4464.9  131.18  4484.9  131.83  4644.9  131.18  4704.9  129.84  4744.9  127.63
  4764.9  127.64  4794.9  129.89  4894.9  129.78  4914.9  129.05  4932.2   129.4
  4942.2  127.18 4944.68  125.37 4959.74  120.26  4981.4  114.05 5000.18  113.23
  5023.3   115.2 5069.06  127.83  5078.6  129.24  5088.6  129.02  5238.6  130.85
  5458.6   131.3  5488.6  132.14  5598.6  131.77  5668.6  134.98  5762.6  135.31
#Mann= 3 ,-1 , 0
  4034.9      .1       0  4914.9     .04       0  5088.6      .1       0
Bank Sta=4932.2,5078.6
XS Rating Curve= 0
Exp/Cntr=.3,.1

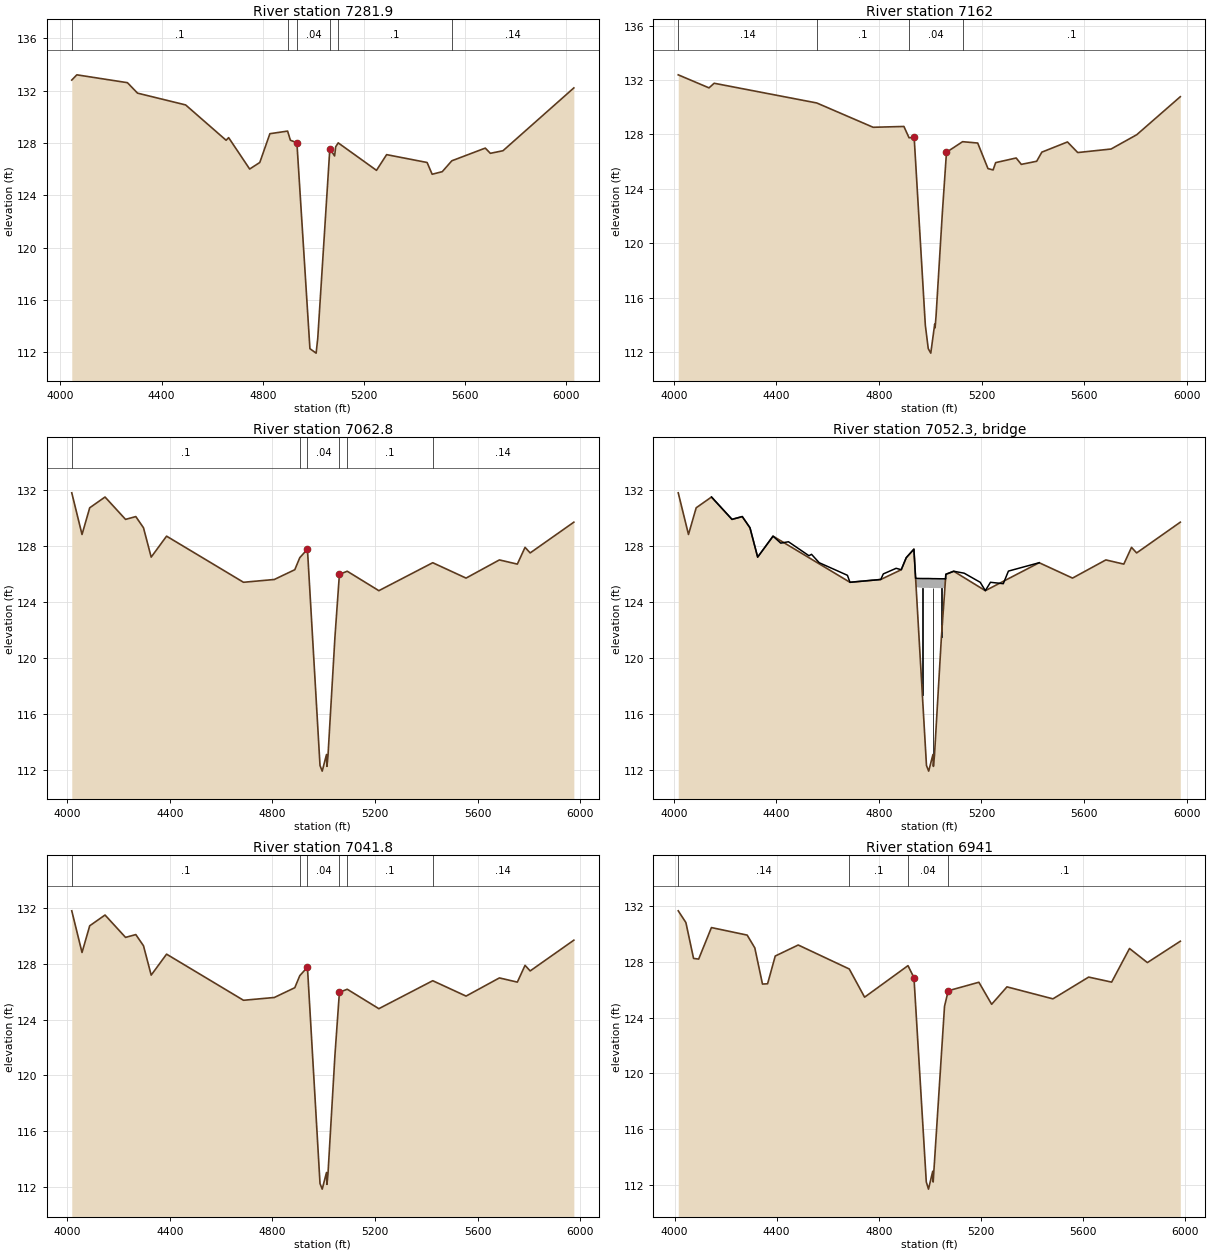
Type RM Length L Ch R = 1 ,7281.9  ,119.9,119.9,119.9
BEGIN DESCRIPTION:
Cross Section K140-00-00-X3
END DESCRIPTION:
XS GIS Cut Line= 4
 3053975.542685113928377.2414616       3053470.7     13927962.82
      3053110.64     13927572.22 3052547.976832113927003.4668706
#Sta/Elev= 30
    4045   132.8    4065   133.2    4265   132.6    4305   131.8    4495   130.9
    4655   128.2    4665   128.4  4748.1     126  4788.1   126.5  4828.1   128.7
  4898.1   128.9  4909.1   128.2  4934.8  128.01  4986.3  112.27  5010.8  111.93
  5017.3  113.08    5065  127.56  5083.8     127  5088.1   127.7  5098.1     128
  5249.4   125.9  5289.4   127.1  5449.4   126.5  5469.4   125.6  5509.4   125.8
  5547.1  126.63  5679.4   127.6  5699.4   127.2  5749.4   127.4  6029.4   132.2
#Mann= 6 ,-1 , 0
    4045      .1       0  4898.1    .045       0  4934.8     .04       0
    5065    .045       0  5098.1      .1       0  5547.1     .14       0
Bank Sta=4934.8,5065
XS Rating Curve= 0
Exp/Cntr=.3,.1

Type RM Length L Ch R = 1 ,7162    ,99.2,99.2,99.2
BEGIN DESCRIPTION:
k140-00-00-s-2-1 PL US - XS 4
END DESCRIPTION:
XS GIS Cut Line= 4
      3054103.35      13928306.6      3053399.95      13927700.1
      3053262.69      13927570.1      3052653.74      13926991.5
#Sta/Elev= 30
    4017  132.39    4137  131.43    4157  131.77    4557  130.32    4777  128.53
    4897  128.59    4917  127.76    4937  127.78 4980.52  113.97 4991.93  112.24
 5001.77  111.91 5017.03  114.04 5018.58  113.77 5022.32  114.64 5047.08  122.29
 5062.98  126.69  5125.8  127.47  5184.8  127.37  5224.8  125.49  5244.8  125.39
  5254.8  125.93  5334.8  126.27  5354.8   125.8  5414.8  126.03  5434.8   126.7
  5534.8  127.45  5574.8  126.67  5704.8  126.93  5804.8  127.98  5974.8  130.78
#Mann= 4 ,-1 , 0
    4017     .14       0    4557      .1       0    4917     .04       0
  5125.8      .1       0
Bank Sta=4937,5062.98
XS Rating Curve= 0
Exp/Cntr=.5,.3

Type RM Length L Ch R = 1 ,7062.8  ,21,21,21
BEGIN DESCRIPTION:
k140-00-00-s-2-1 PL US - XS3
END DESCRIPTION:
XS GIS Cut Line= 5
 3054177.679562913928244.2592795      3053474.28     13927637.78
      3053337.01     13927507.77 3052851.519390113927046.4934851
 3052728.059802713926929.1915084
#Sta/Elev= 30
  4017.7   131.8  4057.7  128.82  4087.7  130.73  4147.4   131.5  4227.4   129.9
  4267.4   130.1  4297.4   129.3  4327.4   127.2  4387.4   128.7  4687.4   125.4
  4807.4   125.6  4887.4   126.3  4906.8  127.16  4936.7  127.77  4985.7  112.29
  4994.3  111.89    5011  113.08  5012.7  112.23  5016.8  112.99  5043.9  121.47
  5061.3  125.97  5091.9  126.19  5215.2   124.8  5425.2   126.8  5555.2   125.7
  5685.2     127  5755.2   126.7  5785.2   127.9  5805.2   127.5  5975.5   129.7
#Mann= 6 ,-1 , 0
  4017.7      .1       0  4906.8    .045       0  4936.7     .04       0
  5061.3    .045       0  5091.9      .1       0  5425.2     .14       0
#XS Ineff= 2 , 0
       0  4926.7   125.4  5071.3       0   124.8
Permanent Ineff=
       F       F
Bank Sta=4936.7,5061.3
XS Rating Curve= 0
Exp/Cntr=.5,.3

Type RM Length L Ch R = 3 ,7052.3  ,,,
BEGIN DESCRIPTION:
PL1_K140-00-00-S2-1
END DESCRIPTION:
Bridge Culvert--1,0,-1,-1, 0
Deck Dist Width WeirC Skew NumUp NumDn MinLoCord MaxHiCord MaxSubmerge Is_Ogee
10,1,2.6,0, 48, 48, , , .95, 0, ,,,
  4147.4  4227.4  4267.4  4297.4  4327.4  4387.4  4417.4  4447.4  4527.4  4537.4
  4567.4  4677.4  4687.4  4807.4  4817.4  4867.4  4887.4  4906.8  4936.7 4943.25
  4945.1 4945.21  4945.3  4969.8  4983.2  4985.7  4994.3    5011  5012.7  5016.8
  5043.9  5044.8  5047.7 5057.47 5059.89 5059.95    5060 5060.06  5061.3  5091.9
  5132.8  5195.2  5215.2  5235.2  5285.2  5305.2  5347.1  5425.2
   131.5   129.9   130.1   129.3   127.2   128.7   128.2   128.3   127.3   127.4
   126.8   125.9   125.4   125.6     126   126.4   126.3  127.16  127.77  125.68
  125.68  125.68  125.68  125.67  125.67  125.67  125.67  125.66  125.66  125.66
  125.65  125.65  125.65  125.65  125.65  125.65  125.63  125.65  125.97  126.19
  126.05   125.4   124.8   125.4   125.3   126.2  126.41   126.8
   131.5   129.9   130.1   129.3   127.2   128.7   128.2   128.3   127.3   127.4
   126.8   125.9   125.4   125.6     126   126.4   126.3  127.16  127.77  125.68
  125.09  125.06  125.03     125     125     125     125  124.99  124.99  124.99
  124.98  124.98  124.98  124.98  125.61  125.62  125.63  125.65  125.97  126.19
  126.05   125.4   124.8   125.4   125.3   126.2  126.41   126.8
  4147.4  4227.4  4267.4  4297.4  4327.4  4387.4  4417.4  4447.4  4527.4  4537.4
  4567.4  4677.4  4687.4  4807.4  4817.4  4867.4  4887.4  4906.8  4936.7 4943.25
  4945.1 4945.21  4945.3  4969.8  4983.2  4985.7  4994.3    5011  5012.7  5016.8
  5043.9  5044.8  5047.7 5057.47 5059.89 5059.95    5060 5060.06  5061.3  5091.9
  5132.8  5195.2  5215.2  5235.2  5285.2  5305.2  5347.1  5425.2
   131.5   129.9   130.1   129.3   127.2   128.7   128.2   128.3   127.3   127.4
   126.8   125.9   125.4   125.6     126   126.4   126.3  127.16  127.77  125.68
  125.68  125.68  125.68  125.67  125.67  125.67  125.67  125.66  125.66  125.66
  125.65  125.65  125.65  125.65  125.65  125.65  125.63  125.65  125.97  126.19
  126.05   125.4   124.8   125.4   125.3   126.2  126.41   126.8
   131.5   129.9   130.1   129.3   127.2   128.7   128.2   128.3   127.3   127.4
   126.8   125.9   125.4   125.6     126   126.4   126.3  127.16  127.77  125.68
  125.09  125.06  125.03     125     125     125     125  124.99  124.99  124.99
  124.98  124.98  124.98  124.98  125.61  125.62  125.63  125.65  125.97  126.19
  126.05   125.4   124.8   125.4   125.3   126.2  126.41   126.8
Pier Skew, UpSta & Num, DnSta & Num=  ,4969.8, 2 ,4969.8, 2 , 0 , 0 , 0 ,,
       1       1
  116.08     126
       1       1
  116.08     126
Pier Skew, UpSta & Num, DnSta & Num=  ,5011, 2 ,5011, 2 , 0 , 0 , 0 ,,
       1       1
  111.83  125.99
       1       1
  111.83  125.99
Pier Skew, UpSta & Num, DnSta & Num=  ,5043.9, 2 ,5043.9, 2 , 0 , 0 , 0 ,,
       1       1
  120.31  125.98
       1       1
  120.31  125.98
BR Coef= 1 , 1 , 1 ,1.25, 0 ,,,.8,0,2,0,
WSPro=,,,, 1 ,,,, 0 ,,,, 0 ,,,,-1 ,-1 ,-1 , 0 , 0 , 0 , 0 , 0
BR D #Sta/Elev= 61
  4017.7   131.8  4037.7  130.65  4057.7  128.82  4067.7  128.92  4087.7  130.73
  4147.4   131.5  4227.4   129.9  4267.4   130.1  4297.4   129.3  4327.4   127.2
  4387.4   128.7  4417.4   128.2  4447.4   128.3  4527.4   127.3  4537.4   127.4
  4567.4   126.8  4677.4   125.9  4687.4   125.4  4807.4   125.6  4817.4     126
  4867.4   126.4  4887.4   126.3  4906.8  127.16  4936.7  127.77 4943.25  125.68
  4945.1  125.09 4945.21  125.06  4945.3  125.03  4969.8  117.24  4983.2  113.03
  4985.7  112.29  4994.3  111.89    5011  113.08  5012.7  112.23  5016.8  112.99
  5043.9  121.47  5044.8   121.7  5047.7  122.45 5057.47  124.98 5059.89  125.61
 5059.95  125.62    5060  125.63 5060.06  125.65  5061.3  125.97  5091.9  126.19
  5132.8  126.05  5195.2   125.4  5215.2   124.8  5235.2   125.4  5285.2   125.3
  5305.2   126.2  5347.1  126.41  5425.2   126.8  5555.2   125.7  5685.2     127
  5705.2   126.7  5745.2   126.9  5755.2   126.7  5785.2   127.9  5805.2   127.5
  5975.5   129.7
BR D #Mann= 6
  4017.7      .1  4906.8    .045  4936.7     .04  5061.3    .045  5091.9      .1
  5425.2     .14
BC Design=,, 0 ,, 0 ,,,,,,
BC HTab HWMax=131.8

Type RM Length L Ch R = 1 ,7041.8  ,102.28,100.8,98.56
BEGIN DESCRIPTION:
k140-00-00-s-2-1 PL DS - XS2
END DESCRIPTION:
XS GIS Cut Line= 5
 3054190.7382347  13928229.11082      3053487.69     13927622.94
      3053350.78     13927493.26 3052865.301643713927032.0011133
 3052741.841296113926914.6999366
#Sta/Elev= 30
  4017.7  131.78  4057.7   128.8  4087.7  130.71  4147.4  131.48  4227.4  129.88
  4267.4  130.08  4297.4  129.28  4327.4  127.18  4387.4  128.68  4687.4  125.38
  4807.4  125.58  4887.4  126.28  4906.8  127.14  4936.7  127.75  4985.7  112.27
  4994.3  111.87    5011  113.06  5012.7  112.21  5016.8  112.97  5043.9  121.45
  5061.3  125.95  5091.9  126.17  5215.2  124.78  5425.2  126.78  5555.2  125.68
  5685.2  126.98  5755.2  126.68  5785.2  127.88  5805.2  127.48  5975.5  129.68
#Mann= 6 ,-1 , 0
  4017.7      .1       0  4906.8    .045       0  4936.7     .04       0
  5061.3    .045       0  5091.9      .1       0  5425.2     .14       0
#XS Ineff= 2 , 0
       0 4930.03  125.38 5067.97       0  124.78
Permanent Ineff=
       F       F
Bank Sta=4936.7,5061.3
XS Rating Curve= 0
Exp/Cntr=.5,.3

Type RM Length L Ch R = 1 ,6941    ,1052.72,1037.5,1014.44
BEGIN DESCRIPTION:
k140-00-00-s-2-1 PL DS - XS 1
END DESCRIPTION:
XS GIS Cut Line= 4
      3054274.65      13928181.1      3053566.39      13927604.4
      3053506.34      13927484.3      3052825.76      13926866.7
#Sta/Elev= 30
  4014.5  131.66  4044.5  130.82  4074.5  128.25  4094.5   128.2  4144.5  130.46
  4284.5  129.92  4314.5     129  4344.5  126.41  4364.5  126.43  4394.5  128.42
  4484.5  129.21  4684.5  127.49  4744.5  125.47  4914.5  127.73  4937.9  126.87
 4986.13  112.23  4994.8  111.71 5011.41  112.99  5013.1  112.22  5057.6  124.82
  5072.2  125.93  5192.2  126.54  5242.2  124.96  5302.2  126.21  5482.2  125.35
  5622.2  126.91  5712.2  126.55  5782.2  128.96  5852.2  127.95  5981.2  129.48
#Mann= 4 ,-1 , 0
  4014.5     .14       0  4684.5      .1       0  4914.5     .04       0
  5072.2      .1       0
Bank Sta=4937.9,5072.2
XS Rating Curve= 0
Exp/Cntr=.3,.1