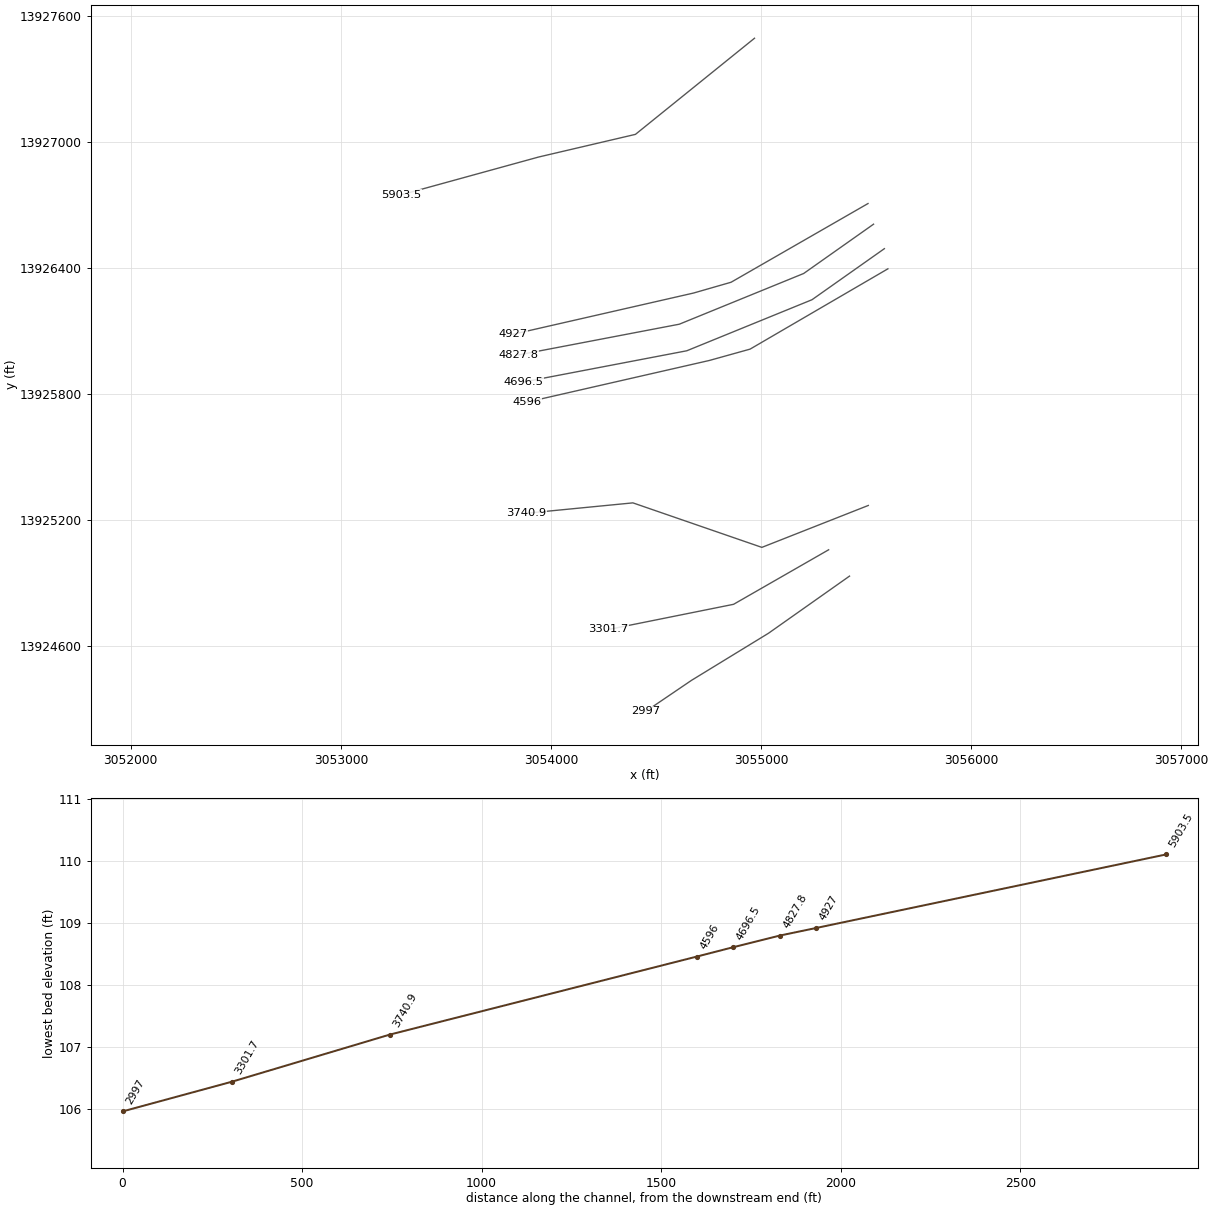
HEC-RAS study K140-00-00.prj: K140-00-00

--- K140-00-00.g01 (geometry) --- (continued)

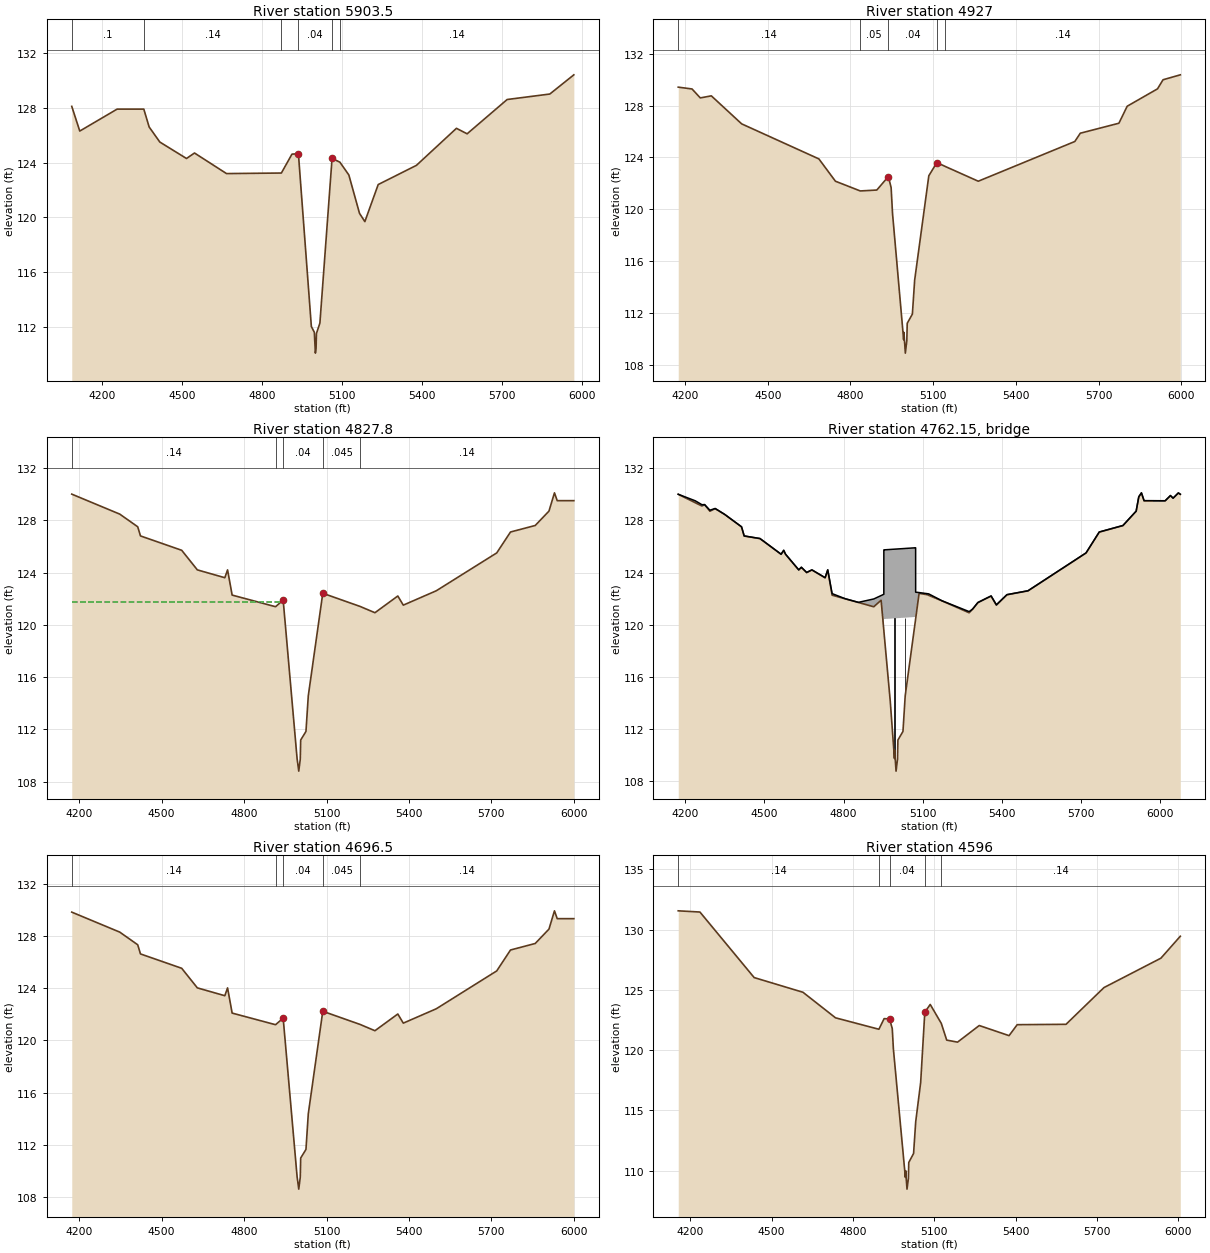
Type RM Length L Ch R = 1 ,5903.5  ,967.79,976.5,985.94
BEGIN DESCRIPTION:
Cross Section K140-00-00-X2
END DESCRIPTION:
XS GIS Cut Line= 4
 3054969.377966813927495.0896502      3054402.55     13927037.46
      3053941.66      13926929.6 3053286.079723913926749.1893164
#Sta/Elev= 30
  4086.9   128.1  4116.9   126.3  4256.9   127.9  4356.9   127.9  4376.9   126.6
  4416.9   125.5  4516.9   124.3  4546.9   124.7  4666.9   123.2  4872.5  123.24
  4912.3  124.62  4936.4  124.64  4984.9  112.05    4996  111.63    5000  110.11
  5002.6  110.46  5003.9  111.54  5016.9   112.3  5062.5  124.31  5091.9  124.03
  5125.4   123.1  5165.4   120.3  5185.4   119.7  5235.4   122.4  5378.7   123.8
  5528.7   126.5  5568.7   126.1  5718.7   128.6  5878.7     129  5968.7   130.4
#Mann= 6 ,-1 , 0
  4086.9      .1       0  4356.9     .14       0  4872.5    .045       0
  4936.4     .04       0  5062.5    .045       0  5091.9     .14       0
#XS Ineff= 2 , 0
       0                    5066       0     124
Permanent Ineff=
       F       F
Bank Sta=4936.4,5062.5
XS Rating Curve= 0
Exp/Cntr=.3,.1

Type RM Length L Ch R = 1 ,4927    ,99.2,99.2,99.2
BEGIN DESCRIPTION:
K140-00-00-S3_LOUETTA -US - XS4
END DESCRIPTION:
XS GIS Cut Line= 4
      3055509.64      13926708.2       3054857.7      13926333.5
      3054678.94      13926282.1      3053818.55      13926085.6
#Sta/Elev= 30
  4175.6  129.42  4225.6  129.28  4255.6  128.59  4295.6  128.75  4405.6  126.59
  4685.6  123.89  4745.6  122.17  4835.6  121.42  4895.6  121.49  4937.5  122.53
  4947.5  121.68 4952.68  119.67 4992.92  109.95 4993.94  110.52 4999.09  108.92
 5004.45  109.88 5005.91  111.22  5024.6  111.93 5032.88  114.55  5084.2  122.59
  5113.5  123.61  5143.5  123.31  5263.5  122.17  5613.5  125.23  5633.5  125.87
  5773.5  126.64  5803.5  127.95  5913.5  129.29  5933.5  129.99  5996.1  130.37
#Mann= 5 ,-1 , 0
  4175.6     .14       0  4835.6     .05       0  4937.5     .04       0
  5113.5     .05       0  5143.5     .14       0
Bank Sta=4937.5,5113.5
XS Rating Curve= 0
Exp/Cntr=.5,.3

Type RM Length L Ch R = 1 ,4827.8  ,131.3,131.3,131.3
BEGIN DESCRIPTION:
K140-00-00-S3_LOUETTA -US - XS3
END DESCRIPTION:
XS GIS Cut Line= 4
      3055536.0113926609.9131723      3055203.38     13926375.24
      3054611.31     13926133.81 3053844.919356513925987.3337566
#Sta/Elev= 30
  4173.1  130.01  4347.7  128.48  4413.1  127.51  4423.1  126.81  4573.1  125.71
    4630  124.21    4730  123.61    4740  124.21  4756.6  122.28  4914.5  121.39
  4942.3  121.89  4992.9  109.77    4999   108.8  5004.5  109.71    5006  111.18
  5025.2  111.84  5033.7  114.57  5086.4  122.42  5222.2  121.41  5276.2  120.93
  5359.4  122.21  5379.4  121.51  5499.4  122.61  5719.4  125.51  5769.4  127.11
  5859.4  127.61  5909.4  128.71  5929.4  130.11  5939.4  129.51  5999.9  129.51
#Mann= 5 ,-1 , 0
  4173.1     .14       0  4914.5    .045       0  4942.3     .04       0
  5086.4    .045       0  5222.2     .14       0
#XS Ineff= 2 , 0
       0  4932.3  121.72  5096.4       0  121.01
Permanent Ineff=
       F       F
Bank Sta=4942.3,5086.4
XS Rating Curve= 0
Exp/Cntr=.5,.3

Type RM Length L Ch R = 3 ,4762.15 ,,,
BEGIN DESCRIPTION:
LOUETTA RD
Structure ID: K140-00-00-S3
END DESCRIPTION:
Bridge Culvert--1,0,-1,-1, 0
Deck Dist Width WeirC Skew NumUp NumDn MinLoCord MaxHiCord MaxSubmerge Is_Ogee
10,112,2.6,0, 55, 55, , , .95, 0, ,,,
  4173.1  4237.7  4263.1  4273.1  4293.1  4313.1  4347.7  4413.1  4423.1  4483.1
  4563.1  4573.1    4580    4630    4640    4660    4680    4730    4740  4756.6
    4806  4856.2  4914.5  4942.3 4952.59  4952.7 4952.91    4953  5072.6 5072.69
  5072.8  5073.2 5073.31  5086.4  5122.7  5173.4  5276.2  5289.4  5309.4  5359.4
  5379.4  5419.4  5499.4  5719.4  5769.4  5859.4  5909.4  5919.4  5929.4  5939.4
  6019.4  6039.4  6049.4  6069.4  6076.8
     130   129.5   129.2  129.21  128.78  128.91  128.48  127.51  126.81  126.61
  125.41  125.71  125.41  124.21  124.41  124.01  124.21  123.61  124.21  122.39
     122  121.72  121.98  122.24  122.34  125.74  125.74  125.74   125.9   125.9
   125.9   125.9   122.5  122.47  122.37  121.84  121.01  121.21  121.71  122.21
  121.54  122.31  122.61  125.51  127.11  127.61  128.71  129.81  130.11  129.51
   129.5   129.9   129.7   130.1     130
     130  129.35   129.1   129.2   128.7   128.9  128.47   127.5   126.8   126.6
   125.4   125.7   125.4   124.2   124.4     124   124.2   123.6   124.2  122.27
  121.99  121.71  121.38  121.88  119.59  119.56  119.52  120.44   120.6   120.6
  120.38  120.44  120.46  122.41  122.26  121.83  120.92   121.2   121.7   122.2
   121.5   122.3   122.6   125.5   127.1   127.6   128.7   129.8   130.1   129.5
   129.5   129.9   129.7   130.1     130
  4173.1  4237.7  4263.1  4273.1  4293.1  4313.1  4347.7  4413.1  4423.1  4483.1
  4563.1  4573.1    4580    4630    4640    4660    4680    4730    4740  4756.6
    4806  4856.2  4914.5  4942.3 4952.59  4952.7 4952.91    4953  5072.6 5072.69
  5072.8  5073.2 5073.31  5086.4  5122.7  5173.4  5276.2  5289.4  5309.4  5359.4
  5379.4  5419.4  5499.4  5719.4  5769.4  5859.4  5909.4  5919.4  5929.4  5939.4
  6019.4  6039.4  6049.4  6069.4  6076.8
     130   129.5   129.2  129.21  128.78  128.91  128.48  127.51  126.81  126.61
  125.41  125.71  125.41  124.21  124.41  124.01  124.21  123.61  124.21  122.39
     122  121.72  121.98  122.24  122.34  125.74  125.74  125.74   125.9   125.9
   125.9   125.9   122.5  122.47  122.37  121.84  121.01  121.21  121.71  122.21
  121.54  122.31  122.61  125.51  127.11  127.61  128.71  129.81  130.11  129.51
   129.5   129.9   129.7   130.1     130
  129.84  129.19  128.94  129.04  128.54  128.74  128.31  127.34  126.64  126.44
  125.24  125.54  125.24  124.04  124.24  123.84  124.04  123.44  124.04  122.11
  121.83  121.55  121.22  121.72  119.43   119.4  119.36  120.28  120.44  120.44
  120.22  120.28   120.3  122.25   122.1  121.67  120.76  121.04  121.54  122.04
  121.34  122.14  122.44  125.34  126.94  127.44  128.54  129.64  129.94  129.34
  129.34  129.74  129.54  129.94  129.84
Pier Skew, UpSta & Num, DnSta & Num=  ,4992.9, 2 ,4992.9, 2 , 0 , 0 , 0 ,,
     1.3     1.3
  108.94  121.49
     1.3     1.3
  108.78  121.33
Pier Skew, UpSta & Num, DnSta & Num=  ,5033.7, 2 ,5033.7, 2 , 0 , 0 , 0 ,,
     1.3     1.3
  113.35  121.55
     1.3     1.3
  113.19  121.39
BR Coef= 1 , 1 , 1 ,1.25, 0 ,,,.8,0,2,0,
WSPro=,,,, 1 ,,,, 0 ,,,, 0 ,,,,-1 ,-1 ,-1 , 0 , 0 , 0 , 0 , 0
BR U #Sta/Elev= 81
  4173.1     130  4237.7  129.35  4263.1   129.1  4273.1   129.2  4287.7  128.84
  4293.1   128.7  4313.1   128.9  4347.7  128.47  4353.1   128.4  4367.7  128.18
  4413.1   127.5  4423.1   126.8  4483.1   126.6  4511.9  126.17  4563.1   125.4
  4571.9  125.66  4573.1   125.7    4580   125.4    4630   124.2  4631.9  124.24
    4640   124.4  4641.9  124.36    4660     124    4680   124.2    4730   123.6
    4740   124.2  4756.6  122.27    4806  121.99  4856.2  121.71  4914.5  121.38
  4942.3  121.88 4952.59  119.59  4952.7  119.56 4952.81  119.54 4952.91  119.52
    4953   119.5  4953.1  119.47    4977  114.15  4992.9  109.76  4993.9  110.39
  4995.5  109.83    4999  108.79  5004.5   109.7    5006  111.17  5025.2  111.83
  5033.7  114.56  5072.6  120.35 5072.69  120.37  5072.8  120.38  5072.9   120.4
 5073.09  120.43  5073.2  120.44 5073.31  120.46  5086.4  122.41  5118.6   122.3
  5122.7  122.26  5173.4  121.83  5222.2   121.4  5276.2  120.92  5289.4   121.2
  5309.4   121.7  5341.9  122.03    5352  122.13  5359.4   122.2  5379.4   121.5
  5419.4   122.3  5499.4   122.6  5719.4   125.5  5769.4   127.1  5859.4   127.6
    5862  127.66  5909.4   128.7  5919.4   129.8  5929.4   130.1  5939.4   129.5
  5999.9   129.5  6019.4   129.5  6039.4   129.9  6049.4   129.7  6069.4   130.1
  6076.8     130
BR U #Mann= 5
  4173.1     .14  4914.5    .045  4942.3     .04  5086.4    .045  5222.2     .14
BR U Banks=4942.3,5086.4
BR D #Sta/Elev= 81
  4173.1  129.84  4237.7  129.19  4263.1  128.94  4273.1  129.04  4287.7  128.68
  4293.1  128.54  4313.1  128.74  4347.7  128.31  4353.1  128.24  4367.7  128.02
  4413.1  127.34  4423.1  126.64  4483.1  126.44  4511.9  126.01  4563.1  125.24
  4571.9   125.5  4573.1  125.54    4580  125.24    4630  124.04  4631.9  124.08
    4640  124.24  4641.9   124.2    4660  123.84    4680  124.04    4730  123.44
    4740  124.04  4756.6  122.11    4806  121.83  4856.2  121.55  4914.5  121.22
  4942.3  121.72 4952.59  119.43  4952.7   119.4 4952.81  119.38 4952.91  119.36
    4953  119.34  4953.1  119.31    4977  113.99  4992.9   109.6  4993.9  110.23
  4995.5  109.67    4999  108.63  5004.5  109.54    5006  111.01  5025.2  111.67
  5033.7   114.4  5072.6  120.19 5072.69  120.21  5072.8  120.22  5072.9  120.24
 5073.09  120.27  5073.2  120.28 5073.31   120.3  5086.4  122.25  5118.6  122.14
  5122.7   122.1  5173.4  121.67  5222.2  121.24  5276.2  120.76  5289.4  121.04
  5309.4  121.54  5341.9  121.87    5352  121.97  5359.4  122.04  5379.4  121.34
  5419.4  122.14  5499.4  122.44  5719.4  125.34  5769.4  126.94  5859.4  127.44
    5862   127.5  5909.4  128.54  5919.4  129.64  5929.4  129.94  5939.4  129.34
  5999.9  129.34  6019.4  129.34  6039.4  129.74  6049.4  129.54  6069.4  129.94
  6076.8  129.84
BR D #Mann= 5
  4173.1     .14  4914.5    .045  4942.3     .04  5086.4    .045  5222.2     .14
BR D Banks=4942.3,5086.4
BC Design=,, 0 ,, 0 ,,,,,,
BC HTab HWMax=130.11

Type RM Length L Ch R = 1 ,4696.5  ,116.74,100.5,80.03
BEGIN DESCRIPTION:
K140-00-00-S3_LOUETTA -DS - XS2
END DESCRIPTION:
XS GIS Cut Line= 4
      3055587.55      13926493.4      3055242.93      13926250.3
       3054646.9      13926007.3      3053868.99      13925858.6
#Sta/Elev= 30
  4173.1  129.82  4347.7  128.29  4413.1  127.32  4423.1  126.62  4573.1  125.52
    4630  124.02    4730  123.42    4740  124.02  4756.6  122.09  4914.5   121.2
  4942.3   121.7  4992.9  109.58    4999  108.61  5004.5  109.52    5006  110.99
  5025.2  111.65  5033.7  114.38  5086.4  122.23  5222.2  121.22  5276.2  120.74
  5359.4  122.02  5379.4  121.32  5499.4  122.42  5719.4  125.32  5769.4  126.92
  5859.4  127.42  5909.4  128.52  5929.4  129.92  5939.4  129.32  5999.9  129.32
#Mann= 5 ,-1 , 0
  4173.1     .14       0  4914.5    .045       0  4942.3     .04       0
  5086.4    .045       0  5222.2     .14       0
#XS Ineff= 2 , 0
       0 4935.63  121.53 5093.07       0  120.82
Permanent Ineff=
       F       F
Bank Sta=4942.3,5086.4
XS Rating Curve= 0
Exp/Cntr=.5,.3

Type RM Length L Ch R = 1 ,4596    ,993.26,855.1,680.97
BEGIN DESCRIPTION:
K140-00-00-S3_LOUETTA -DS - XS1
END DESCRIPTION:
XS GIS Cut Line= 4
      3055604.33      13926397.5       3054948.3      13926015.2
      3054754.85      13925961.3      3053885.78      13925762.7
#Sta/Elev= 30
  4155.5  131.56  4235.5  131.46  4435.5  126.02  4615.5   124.8  4735.5  122.68
  4895.5  121.73  4914.8  122.61  4934.8  122.59  4944.8  121.79 4948.99  120.09
 4993.12  109.44 4994.11  109.99  4999.2  108.46 5004.28  109.34 5005.67  110.67
 5023.42  111.42 5031.28  114.05 5049.58  117.32  5064.8  123.14  5084.8  123.79
  5125.6  122.22  5145.6  120.83  5185.6  120.66  5265.6  122.04  5375.6   121.2
  5405.6  122.11  5585.6  122.14  5725.6  125.19  5935.6  127.63  6007.1  129.45
#Mann= 5 ,-1 , 0
  4155.5     .14       0  4895.5     .05       0  4934.8     .04       0
  5064.8     .05       0  5125.6     .14       0
Bank Sta=4934.8,5064.8
XS Rating Curve= 0
Exp/Cntr=.3,.1

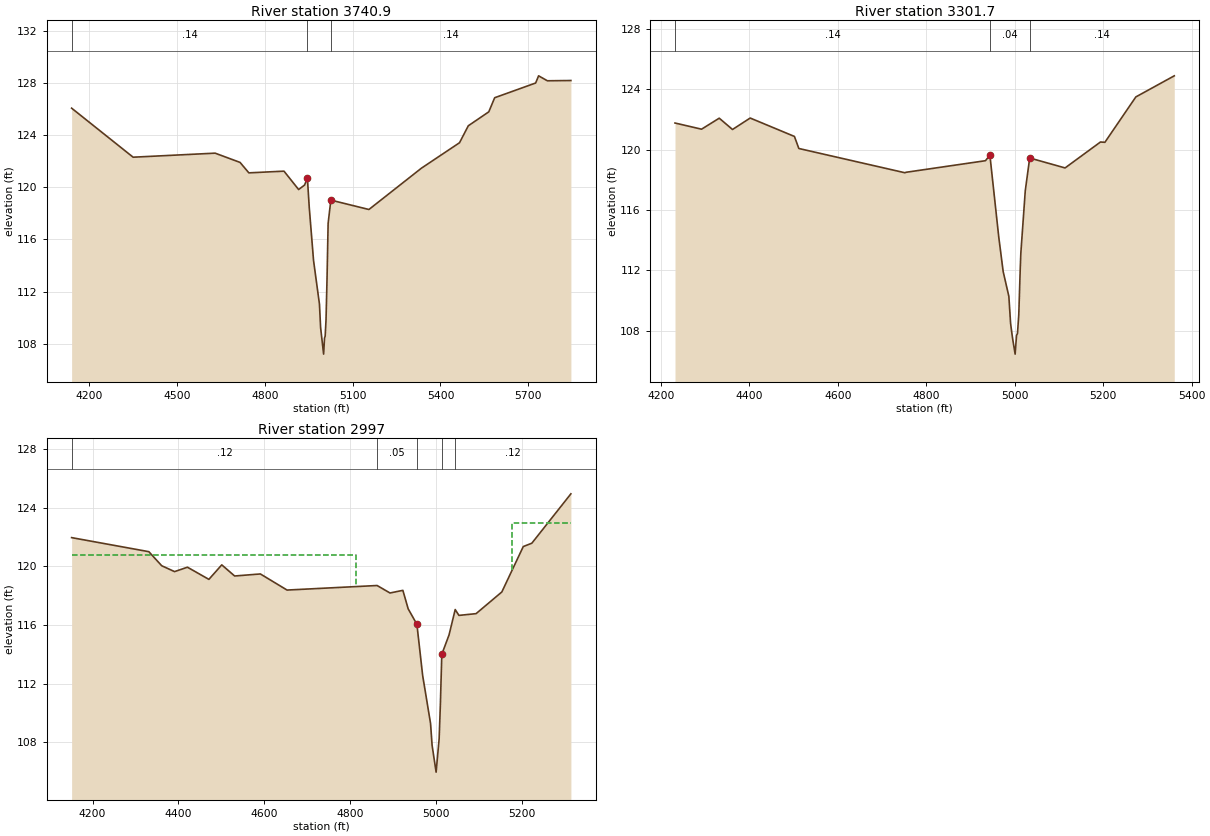
Type RM Length L Ch R = 1 ,3740.9  ,351,439.2,510
BEGIN DESCRIPTION:
Interpolated XS
END DESCRIPTION:
XS GIS Cut Line= 4
        3055511.       13925271.      3055004.35     13925071.45
      3054390.46     13925283.32      3053882.55     13925233.76
#Sta/Elev= 30
  4140.4  126.06  4350.4   122.3  4630.4  122.61  4715.6   121.9  4745.6   121.1
  4865.6  121.23  4915.6  119.82  4935.6  120.16  4945.6  120.68  4951.8  118.46
  4966.5  114.38  4986.7  111.03  4990.6  109.24  5000.9   107.2    5004  108.43
  5006.2  108.58  5009.1  109.81  5012.5  112.93  5016.3  117.23  5025.6  119.01
  5155.6  118.29    5335  121.46    5465  123.41    5495  124.71    5565  125.78
    5585  126.86    5725  127.99    5735  128.54    5765  128.16  5845.3  128.18
#Mann= 3 ,-1 , 0
  4140.4     .14       0  4945.6     .04       0  5025.6     .14       0
Bank Sta=4945.6,5025.6
XS Rating Curve= 0
Exp/Cntr=.3,.1

Type RM Length L Ch R = 1 ,3301.7  ,225.7,304.7,304.7
BEGIN DESCRIPTION:
interpolated XS
END DESCRIPTION:
XS GIS Cut Line= 3
       3055322.2       13925060.      3054869.65     13924800.44
      3054274.59     13924680.68
#Sta/Elev= 30
  4231.8  121.77  4291.8  121.36  4331.8  122.09  4361.8  121.34  4401.8   122.1
  4501.8  120.88  4511.8  120.08  4751.8  118.47  4753.8   118.5  4933.8  119.27
  4943.8  119.64  4963.8  114.22  4973.8  111.92  4986.7  110.27  4990.6  108.48
  4993.8  107.76  4995.5  107.41  5000.9  106.44    5004  107.67  5006.2  107.82
  5009.1  109.05  5012.5  112.17  5013.8  113.15  5023.8  117.28  5033.8  119.45
  5113.8  118.79  5193.8  120.51  5203.8  120.49  5273.8   123.5  5360.7   124.9
#Mann= 3 ,-1 , 0
  4231.8     .14       0  4943.8     .04       0  5033.8     .14       0
Bank Sta=4943.8,5033.8
XS Rating Curve= 0
Exp/Cntr=.3,.1

Type RM Length L Ch R = 1 ,2997    ,99.8,99.3,99.3
BEGIN DESCRIPTION:
K140-00-00-S1B_RIVER PARK WB -US - XS4
END DESCRIPTION:
XS GIS Cut Line= 4
      3055421.58      13924934.7      3055035.73      13924662.6
      3054669.51      13924438.6      3054453.56      13924292.1
#Sta/Elev= 30
  4151.2  121.97  4331.2  121.01  4361.2  120.05  4391.2  119.65  4421.2  119.95
  4471.2  119.12  4501.2  120.11  4531.2  119.35  4591.2  119.49  4653.4  118.39
  4863.4   118.7  4893.4  118.19  4923.4  118.37 4935.76  117.11 4956.11  116.05
 4969.52  112.56 4987.95  109.28  4991.5   107.8  5000.9  105.96 5007.95  108.24
 5010.88  110.61 5014.14     114 5031.08  115.33  5045.4  117.06  5054.1  116.66
  5094.1  116.78  5154.1  118.26  5204.1  121.36  5224.1  121.59  5315.1  124.96
#Mann= 5 ,-1 , 0
  4151.2     .12       0  4863.4     .05       0 4956.11     .04       0
 5014.14     .05       0  5045.4     .12       0
#XS Ineff= 2 , 0
       0    4814   120.8    5178       0     123
Permanent Ineff=
       F       F
Bank Sta=4956.11,5014.14
XS Rating Curve= 0
Exp/Cntr=.5,.3