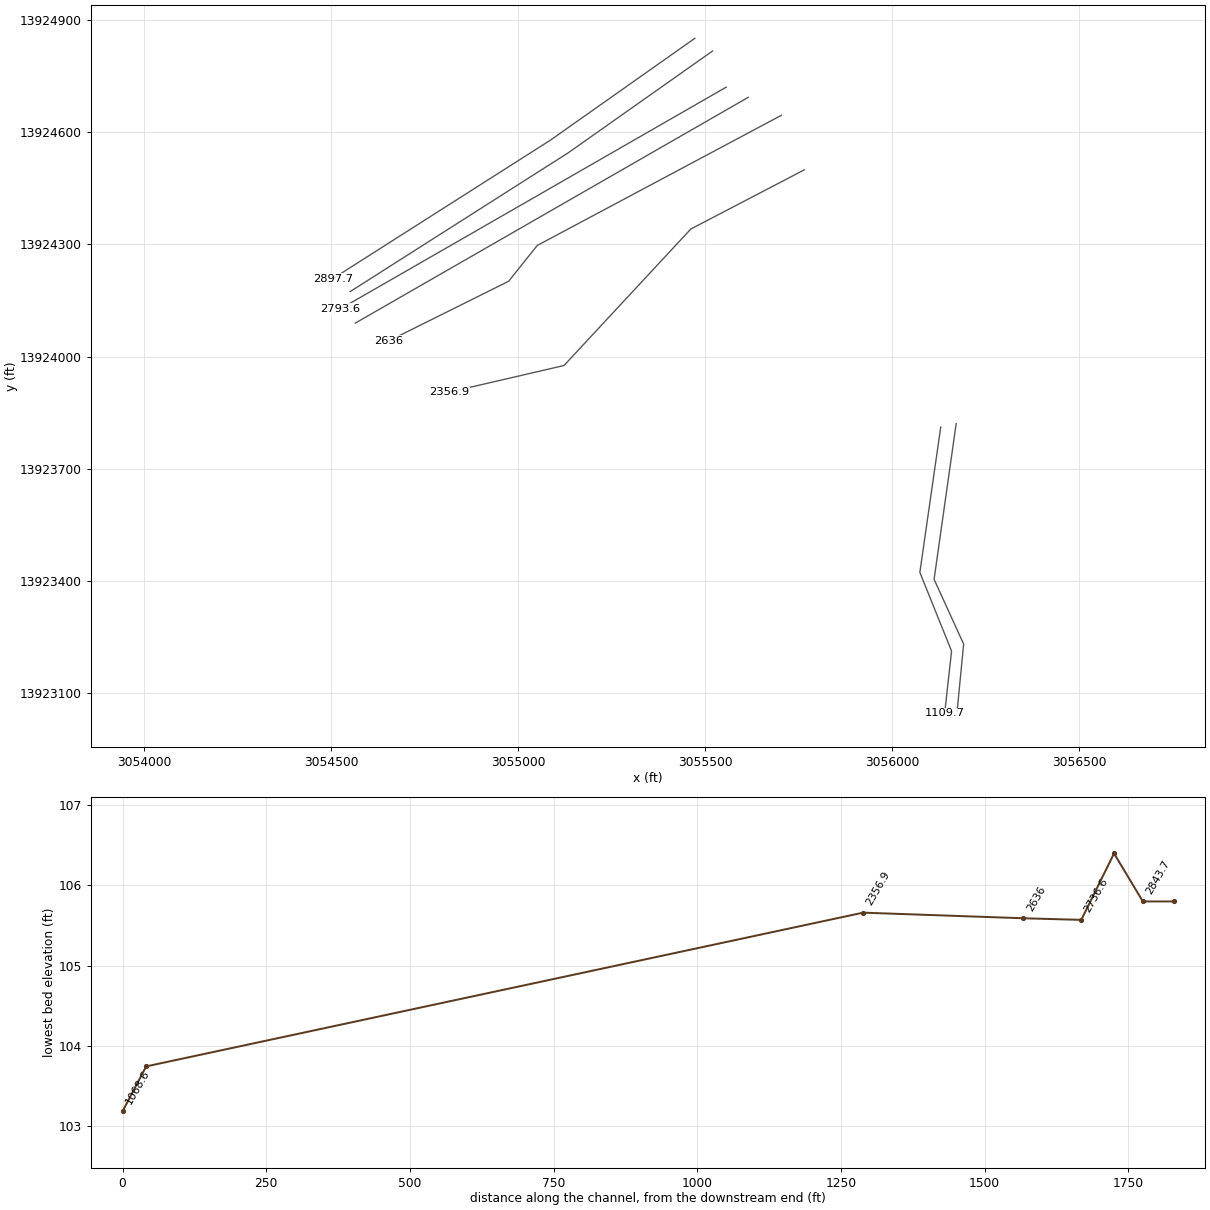
HEC-RAS study K140-00-00.prj: K140-00-00

--- K140-00-00.g01 (geometry) --- (continued)

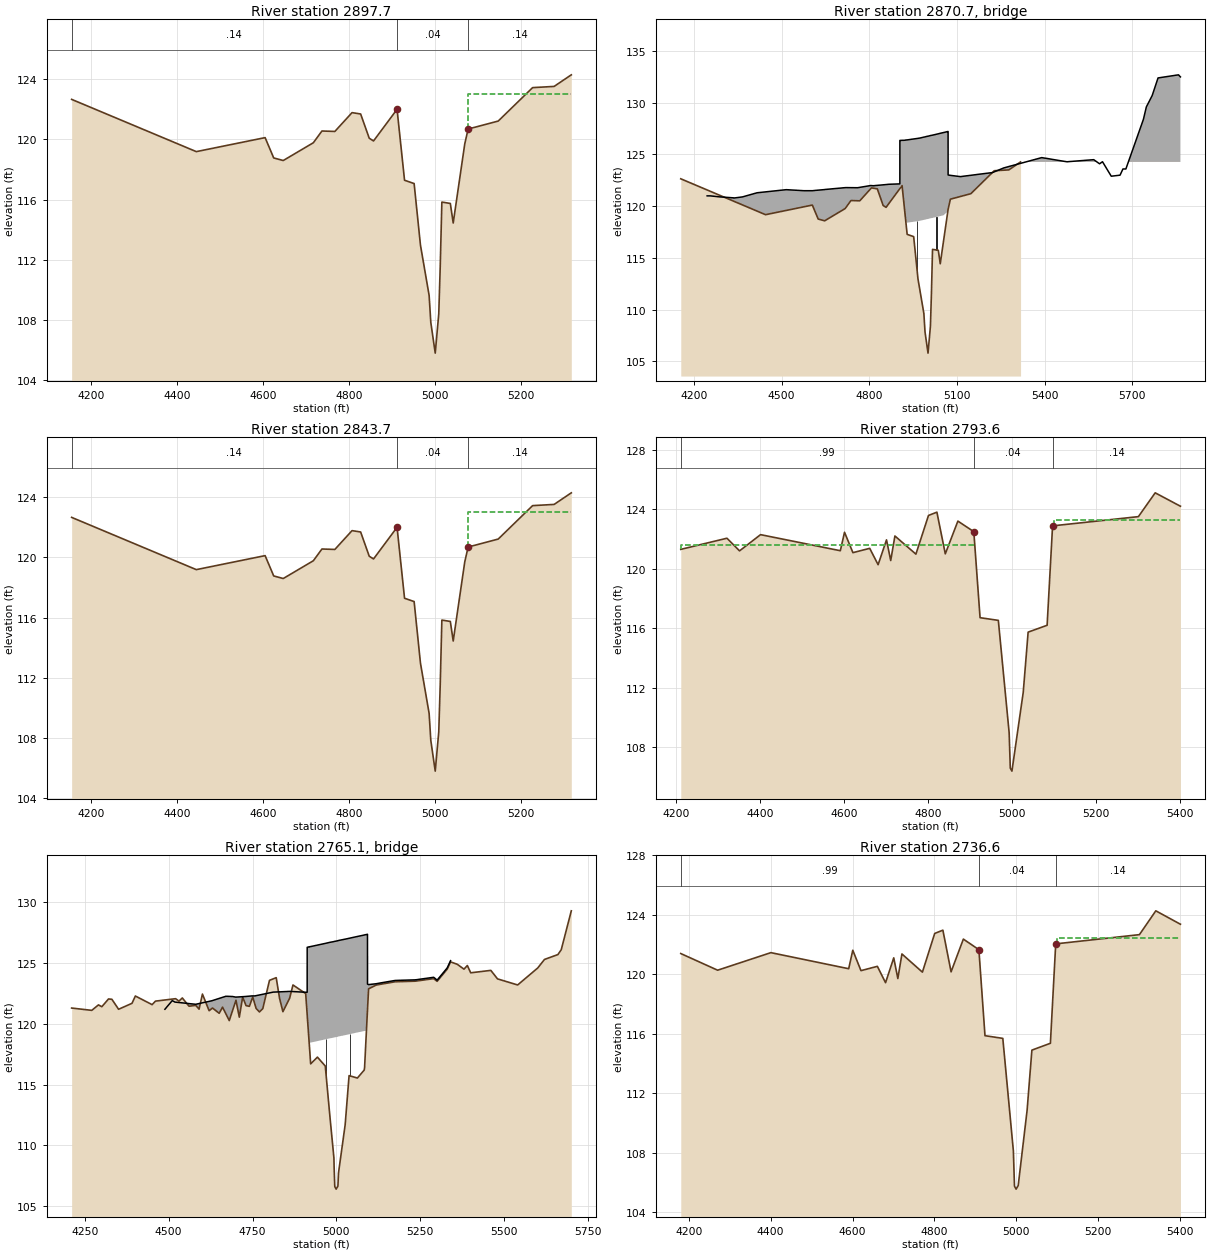
Type RM Length L Ch R = 1 ,2897.7  ,54,54,54
BEGIN DESCRIPTION:
K140-00-00-S1B_RIVER PARK WB -US - XS3
END DESCRIPTION:
XS GIS Cut Line= 3
 3055471.925638713924850.8754412      3055086.08     13924578.74
      3054503.91      13924208.2
#Sta/Elev= 30
  4155.2  122.65  4445.2  119.18  4605.2  120.11  4625.2  118.76  4647.4  118.59
  4717.4  119.77  4737.4  120.55  4767.4  120.52  4807.4  121.77  4827.4  121.68
  4847.4  120.07  4857.4  119.89  4912.1  121.99  4929.5  117.28  4951.8  117.06
  4966.5  112.98  4986.7  109.63  4990.6  107.84  5000.9   105.8  5009.1  108.41
  5012.5  111.53  5016.3  115.83    5036  115.74  5042.7  114.44 5069.61   119.7
  5077.4  120.68  5147.4  121.21  5227.4  123.43  5277.4  123.51  5317.4  124.28
#Mann= 3 ,-1 , 0
  4155.2     .14       0  4912.1     .04       0  5077.4     .14       0
#XS Ineff= 2 , 0
       0    4914   120.8    5078       0     123
Permanent Ineff=
       F       F
Bank Sta=4912.1,5077.4
XS Rating Curve= 0
Exp/Cntr=.5,.3

Type RM Length L Ch R = 3 ,2870.7  ,,,
BEGIN DESCRIPTION:
RIVER PARK WB (previously Compaq Center)
Structure ID: K140-00-00-S1B
END DESCRIPTION:
Bridge Culvert--1,0,-1,-1, 0
Deck Dist Width WeirC Skew NumUp NumDn MinLoCord MaxHiCord MaxSubmerge Is_Ogee
10,34,2.6,0, 92, 92, , , .95, 0, ,,,
  4245.4  4256.1  4285.4  4335.4  4336.1  4366.1  4416.1  4516.1  4576.1  4585.4
  4605.4  4606.1  4615.4  4627.6  4647.6  4648.7    4654  4679.8  4700.6  4707.2
  4719.8  4752.3  4760.4  4804.9  4813.5  4859.9  4865.8 4904.49  4904.6 4904.71
  4912.1  4918.6 4924.41  4924.5 4924.65  4924.9  4929.5  4951.8  4966.5  4973.3
  4986.7  4990.6  4993.8  4995.5  5000.9    5004  5006.2  5009.1  5012.5  5016.3
    5036  5042.7  5053.8  5068.6 5068.69  5068.8  5068.9 5069.39  5069.5 5069.61
  5075.8  5111.9  5116.6  5164.3  5169.1  5217.9  5221.2  5259.8  5272.6  5273.1
  5277.6  5327.6  5389.8  5397.6  5407.6  5427.6  5457.6 5477.27  5477.6  5567.6
  5587.6  5597.6  5627.6  5657.6  5667.6  5677.6  5737.6  5747.6  5767.6  5787.6
  5857.6  5864.2
     121     121  120.91  120.81  120.79   120.9   121.3   121.6   121.5   121.5
   121.5   121.5  121.53  121.56  121.61  121.62  121.63   121.7  121.75  121.77
   121.8  121.79  121.79     122  121.98   122.1  122.12  122.16  126.36  126.36
  126.37  126.37  126.39  126.39  126.39   126.4  126.41   126.5  126.56  126.59
  126.68   126.7  126.73  126.74  126.77  126.79  126.81  126.83  126.85  126.87
     127  127.05  127.12  127.22  127.22  127.22  127.22  127.22  127.22  123.02
  122.99  122.86  122.88  123.05  123.07  123.24  123.25   123.7   123.8   123.8
  123.84  124.22   124.7  124.66  124.62  124.52  124.38  124.29   124.3   124.5
   124.1   124.3   122.9     123   123.6   123.6   128.4   129.6   130.7   132.4
   132.7   132.5
                                                                                
                                                                                
                                                          121.95  121.95  121.95
  121.97  120.12  118.47  118.44   118.4   118.4  118.41   118.5  118.56  118.59
  118.68   118.7  118.73  118.74  118.77  118.79  118.81  118.83  118.85  118.87
     119  119.05  119.12  119.29  119.32  119.37  119.41  119.59  119.64  119.68
                                                                                
                                                                                
                                                                                
                
  4245.4  4256.1  4285.4  4335.4  4336.1  4366.1  4416.1  4516.1  4576.1  4585.4
  4605.4  4606.1  4615.4  4627.6  4647.6  4648.7    4654  4679.8  4700.6  4707.2
  4719.8  4752.3  4760.4  4804.9  4813.5  4859.9  4865.8 4904.49  4904.6 4904.71
  4912.1  4918.6 4924.41  4924.5 4924.65  4924.9  4929.5  4951.8  4966.5  4973.3
  4986.7  4990.6  4993.8  4995.5  5000.9    5004  5006.2  5009.1  5012.5  5016.3
    5036  5042.7  5053.8  5068.6 5068.69  5068.8  5068.9 5069.39  5069.5 5069.61
  5075.8  5111.9  5116.6  5164.3  5169.1  5217.9  5221.2  5259.8  5272.6  5273.1
  5277.6  5327.6  5389.8  5397.6  5407.6  5427.6  5457.6 5477.27  5477.6  5567.6
  5587.6  5597.6  5627.6  5657.6  5667.6  5677.6  5737.6  5747.6  5767.6  5787.6
  5857.6  5864.2
     121     121  120.91  120.81  120.79   120.9   121.3   121.6   121.5   121.5
   121.5   121.5  121.53  121.56  121.61  121.62  121.63   121.7  121.75  121.77
   121.8  121.79  121.79     122  121.98   122.1  122.12  122.16  126.36  126.36
  126.37  126.37  126.39  126.39  126.39   126.4  126.41   126.5  126.56  126.59
  126.68   126.7  126.73  126.74  126.77  126.79  126.81  126.83  126.85  126.87
     127  127.05  127.12  127.22  127.22  127.22  127.22  127.22  127.22  123.02
  122.99  122.86  122.88  123.05  123.07  123.24  123.25   123.7   123.8   123.8
  123.84  124.22   124.7  124.66  124.62  124.52  124.38  124.29   124.3   124.5
   124.1   124.3   122.9     123   123.6   123.6   128.4   129.6   130.7   132.4
   132.7   132.5
                                                                                
                                                                                
                                                          121.95  121.95  121.95
  121.97  120.12  118.47  118.44   118.4   118.4  118.41   118.5  118.56  118.59
  118.68   118.7  118.73  118.74  118.77  118.79  118.81  118.83  118.85  118.87
     119  119.05  119.12  119.29  119.32  119.37  119.41  119.59  119.64  119.68
                                                                                
                                                                                
                                                                                
                
Pier Skew, UpSta & Num, DnSta & Num=  ,4963.3, 2 ,4963.3, 2 , 0 , 0 , 0 ,,
     1.4     1.4
  112.65  119.55
     1.4     1.4
  112.65  119.55
Pier Skew, UpSta & Num, DnSta & Num=  ,5030.3, 2 ,5030.3, 2 , 0 , 0 , 0 ,,
     1.4     1.4
  114.74  119.97
     1.4     1.4
  114.74  119.97
BR Coef= 1 , 1 , 1 ,1.25, 0 ,,,.8,0,2,0,
WSPro=,,,, 1 ,,,, 0 ,,,, 0 ,,,,-1 ,-1 ,-1 , 0 , 0 , 0 , 0 , 0
BC Design=,, 0 ,, 0 ,,,,,,
BC HTab HWMax=124.28

Type RM Length L Ch R = 1 ,2843.7  ,63,50.1,41
BEGIN DESCRIPTION:
K140-00-00-S1B_RIVER PARK WB -DS - XS2
END DESCRIPTION:
XS GIS Cut Line= 3
 3055519.256929213924816.8836116      3055133.02     13924544.47
      3054550.45      13924173.7
#Sta/Elev= 30
  4155.2  122.65  4445.2  119.18  4605.2  120.11  4625.2  118.76  4647.4  118.59
  4717.4  119.77  4737.4  120.55  4767.4  120.52  4807.4  121.77  4827.4  121.68
  4847.4  120.07  4857.4  119.89  4912.1  121.99  4929.5  117.28  4951.8  117.06
  4966.5  112.98  4986.7  109.63  4990.6  107.84  5000.9   105.8  5009.1  108.41
  5012.5  111.53  5016.3  115.83    5036  115.74  5042.7  114.44 5069.61   119.7
  5077.4  120.68  5147.4  121.21  5227.4  123.43  5277.4  123.51  5317.4  124.28
#Mann= 3 ,-1 , 0
  4155.2     .14       0  4912.1     .04       0  5077.4     .14       0
#XS Ineff= 2 , 0
       0    4914   120.8    5078       0     123
Permanent Ineff=
       F       F
Bank Sta=4912.1,5077.4
XS Rating Curve= 0
Exp/Cntr=.5,.3

Type RM Length L Ch R = 1 ,2793.6  ,57,57,57
BEGIN DESCRIPTION:
K140-00-00-S1A_RIVER PARK EB -DS - XS3
END DESCRIPTION:
XS GIS Cut Line= 2
 3055555.907163613924720.3609774      3054524.05      13924127.4
#Sta/Elev= 30
  4210.7   121.3  4320.7  122.05  4350.7   121.2  4400.7  122.29  4590.7  121.21
  4600.7  122.45  4620.7  121.08  4660.7  121.37  4680.7  120.27  4700.7  121.94
  4710.7  120.55  4720.7   122.2  4770.7  120.98  4800.7  123.58  4820.7   123.8
  4840.7     121  4870.7   123.2  4908.6  122.49  4923.5  116.71    4967  116.53
  4992.8  108.97  4995.5   106.6  4999.4   106.4  5026.3  111.69    5038  115.74
  5083.2   116.2  5096.2  122.88  5300.6   123.5  5340.6   125.1  5400.7   124.2
#Mann= 3 ,-1 , 0
  4210.7     .99       0  4908.6     .04       0  5096.2     .14       0
#XS Ineff= 2 , 0
       0    4909   121.6    5099       0   123.3
Permanent Ineff=
       F       F
Bank Sta=4908.6,5096.2
XS Rating Curve= 0
Exp/Cntr=.5,.3

Type RM Length L Ch R = 3 ,2765.1  ,,,
BEGIN DESCRIPTION:
RIVER PARK EB (previously Compaq Center)
Structure ID: K140-00-00-S1A
END DESCRIPTION:
Bridge Culvert--1,0,-1,-1, 0
Deck Dist Width WeirC Skew NumUp NumDn MinLoCord MaxHiCord MaxSubmerge Is_Ogee
10,37,2.6,0, 61, 61, , , .95, 0, ,,,
  4488.8  4510.6  4518.8  4580.6  4600.6  4620.6  4628.8  4670.6  4690.6    4700
  4728.8  4748.8  4756.8  4757.1  4809.9    4811  4860.8  4860.9  4908.6 4912.99
  4913.1 4913.21 4919.01  4919.1 4919.24  4923.3  4923.5  4943.6    4967  4981.2
  4992.8  4993.4  4995.1  4995.5  4999.4  5004.6  5004.9  5006.5  5026.3    5038
  5062.8  5083.2  5084.3 5089.49  5089.6  5089.7 5092.79  5092.9 5093.01  5096.2
  5118.7  5130.4    5175  5185.6    5234    5238  5290.2  5291.2  5300.6  5330.6
  5340.6
   121.2  121.91  121.79  121.61  121.73  121.85   121.9  122.27  122.25   122.2
  122.25   122.3   122.3   122.3   122.6  122.61  122.67  122.67   122.6   122.6
   126.3   126.3  126.33  126.34  126.34  126.36  126.36  126.48  126.62  126.71
  126.77  126.78  126.79  126.79  126.81  126.84  126.85  126.86  126.97  127.04
  127.19  127.31  127.32  127.35  127.35  127.35  127.37  127.37  123.27  123.23
   123.3  123.36  123.57  123.58  123.62  123.63  123.83  123.81   123.6   124.6
   125.2
                                                                                
                                                                                
                                  118.44  118.46  118.46  118.58  118.72  118.81
  118.87  118.88  118.89  118.89  118.91  118.94  118.95  118.96  119.07  119.14
  119.29  119.41  119.42  119.45  119.45
                                                                                
        
  4488.8  4510.6  4518.8  4580.6  4600.6  4620.6  4628.8  4670.6  4690.6    4700
  4728.8  4748.8  4756.8  4757.1  4809.9    4811  4860.8  4860.9  4908.6 4912.99
  4913.1 4913.21 4919.01  4919.1 4919.24  4923.3  4923.5  4943.6    4967  4981.2
  4992.8  4993.4  4995.1  4995.5  4999.4  5004.6  5004.9  5006.5  5026.3    5038
  5062.8  5083.2  5084.3 5089.49  5089.6  5089.7 5092.79  5092.9 5093.01  5096.2
  5118.7  5130.4    5175  5185.6    5234    5238  5290.2  5291.2  5300.6  5330.6
  5340.6
   121.2  121.91  121.79  121.61  121.73  121.85   121.9  122.27  122.25   122.2
  122.25   122.3   122.3   122.3   122.6  122.61  122.67  122.67   122.6   122.6
   126.3   126.3  126.33  126.34  126.34  126.36  126.36  126.48  126.62  126.71
  126.77  126.78  126.79  126.79  126.81  126.84  126.85  126.86  126.97  127.04
  127.19  127.31  127.32  127.35  127.35  127.35  127.37  127.37  123.27  123.23
   123.3  123.36  123.57  123.58  123.62  123.63  123.83  123.81   123.6  123.67
   124.3
                                                                                
                                                                                
                                  117.51  117.53  117.53  117.65  117.79  117.88
  117.94  117.95  117.96  117.96  117.98  118.01  118.02  118.03  118.14  118.21
  118.36  118.48  118.49  118.52  118.52
                                                                                
        
Pier Skew, UpSta & Num, DnSta & Num=  ,4969.9, 2 ,4969.9, 2 , 0 , 0 , 0 ,,
     1.4     1.4
  114.55  119.74
     1.4     1.4
  113.62  118.81
Pier Skew, UpSta & Num, DnSta & Num=  ,5040.1, 2 ,5040.1, 2 , 0 , 0 , 0 ,,
     1.4     1.4
  114.82  120.16
     1.4     1.4
  113.89  119.23
BR Coef= 1 , 1 , 1 ,1.25, 0 ,,,.8,0,2,0,
WSPro=,,,, 1 ,,,, 0 ,,,, 0 ,,,,-1 ,-1 ,-1 , 0 , 0 , 0 , 0 , 0
BR U #Sta/Elev= 92
  4210.7   121.3  4270.7  121.11  4290.7  121.56  4300.7  121.41  4320.7  122.05
  4330.7  122.02  4350.7   121.2  4390.7  121.69  4400.7  122.29  4450.7  121.58
  4460.7  121.87  4520.7  122.07  4530.7  121.87  4540.7  122.13  4560.7  121.45
  4580.7  121.52  4590.7  121.21  4600.7  122.45  4620.7  121.08  4630.7   121.3
  4650.7  120.87  4660.7  121.37  4680.7  120.27  4700.7  121.94  4710.7  120.55
  4720.7   122.2  4730.7   121.5  4740.7  121.44  4750.7  122.21  4760.7  121.27
  4770.7  120.98  4780.7  121.25  4800.7  123.58  4820.7   123.8  4830.7   122.1
  4840.7     121  4860.7   122.1  4870.7   123.2  4908.6  122.49 4912.99  120.78
  4913.1  120.73 4913.21  120.69    4919  118.43  4919.1  118.39  4919.3  118.34
  4923.3  116.76  4923.5  116.71  4943.6  117.26    4967  116.53  4981.2  112.28
  4992.8  108.97  4993.4  108.23  4995.1  106.79  4995.5   106.6  4999.4   106.4
  5004.6  106.64  5004.9  106.76  5006.5  107.74  5026.3  111.69    5038  115.74
  5062.8  115.54  5083.2   116.2  5084.3  116.43 5089.49  119.29  5089.7   119.4
 5092.79  121.06  5092.9  121.11 5093.01  121.17  5096.2  122.88  5118.7  123.19
  5130.4  123.25    5175  123.46  5185.6  123.47    5234  123.51    5238  123.52
  5290.2  123.72  5291.2   123.7  5300.6   123.5  5330.6   124.5  5340.6   125.1
  5360.7   124.9  5380.7   124.5  5390.7   124.8  5400.7   124.2  5460.7   124.4
  5480.7   123.7  5540.7   123.2  5600.7   124.6  5620.7   125.3  5660.7   125.7
  5670.7   126.1  5700.7   129.3
BR U #Mann= 3
  4210.7     .99  4908.6     .04  5096.2     .14
BR D #Sta/Elev= 93
  4180.7   121.4  4210.7  120.47  4270.7  120.28  4290.7  120.73  4300.7  120.58
  4320.7  121.22  4330.7  121.19  4350.7  120.37  4390.7  120.86  4400.7  121.46
  4450.7  120.75  4460.7  121.04  4520.7  121.24  4530.7  121.04  4540.7   121.3
  4560.7  120.62  4580.7  120.69  4590.7  120.38  4600.7  121.62  4620.7  120.25
  4630.7  120.47  4650.7  120.04  4660.7  120.54  4680.7  119.44  4700.7  121.11
  4710.7  119.72  4720.7  121.37  4730.7  120.67  4740.7  120.61  4750.7  121.38
  4760.7  120.44  4770.7  120.15  4780.7  120.42  4800.7  122.75  4820.7  122.97
  4830.7  121.27  4840.7  120.17  4860.7  121.27  4870.7  122.37  4908.6  121.66
 4912.99  119.95  4913.1   119.9 4913.21  119.86    4919   117.6    4919  117.56
  4919.3  117.51  4923.3  115.93  4923.5  115.88  4943.6  116.43    4967   115.7
  4981.2  111.45  4992.8  108.14  4993.4   107.4  4995.1  105.96  4995.5  105.77
  4999.4  105.57  5004.6  105.81  5004.9  105.93  5006.5  106.91  5026.3  110.86
    5038  114.91  5062.8  114.71  5083.2  115.37  5084.3   115.6 5089.49  118.46
  5089.7  118.57 5092.79  120.23  5092.9  120.28 5093.01  120.34  5096.2  122.05
  5118.7  122.36  5130.4  122.42    5175  122.63  5185.6  122.64    5234  122.68
    5238  122.69  5290.2  122.89  5291.2  122.87  5300.6  122.67  5330.6  123.67
  5340.6  124.27  5360.7  124.07  5380.7  123.67  5390.7  123.97  5400.7  123.37
  5460.7  123.57  5480.7  122.87  5540.7  122.37  5600.7  123.77  5620.7  124.47
  5660.7  124.87  5670.7  125.27  5700.7  128.47
BR D #Mann= 3
  4180.7     .99  4908.6     .04  5096.2     .14
BC Design=,, 0 ,, 0 ,,,,,,
BC HTab HWMax=125.1

Type RM Length L Ch R = 1 ,2736.6  ,90.61,100.6,112.6
BEGIN DESCRIPTION:
K140-00-00-S1A_RIVER PARK EB -DS - XS2
END DESCRIPTION:
XS GIS Cut Line= 2
 3055614.785190613924693.0705016      3054564.12      13924089.4
#Sta/Elev= 30
  4180.7   121.4  4270.7  120.28  4400.7  121.46  4590.7  120.38  4600.7  121.62
  4620.7  120.25  4660.7  120.54  4680.7  119.44  4700.7  121.11  4710.7  119.72
  4720.7  121.37  4770.7  120.15  4800.7  122.75  4820.7  122.97  4840.7  120.17
  4870.7  122.37  4908.6  121.66  4923.5  115.88    4967   115.7  4992.8  108.14
  4995.5  105.77  4999.4  105.57  5004.6  105.81  5026.3  110.86    5038  114.91
  5083.2  115.37  5096.2  122.05  5300.6  122.67  5340.6  124.27  5400.7  123.37
#Mann= 3 ,-1 , 0
  4180.7     .99       0  4908.6     .04       0  5096.2     .14       0
#XS Ineff= 2 , 0
       0    4909  120.77    5099       0  122.47
Permanent Ineff=
       F       F
Bank Sta=4908.6,5096.2
XS Rating Curve= 0
Exp/Cntr=.5,.3

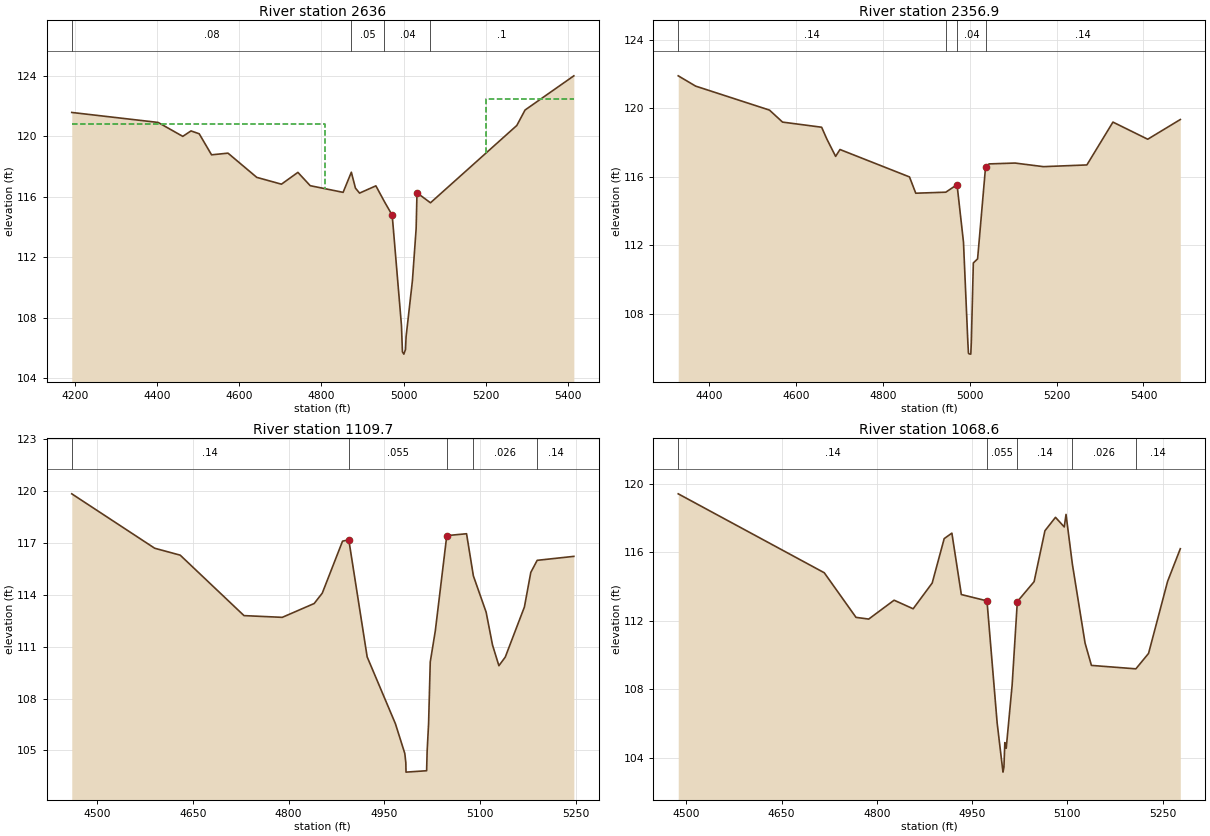
Type RM Length L Ch R = 1 ,2636    ,251.39,279.1,312.4
BEGIN DESCRIPTION:
K140-00-00-S1A_RIVER PARK EB -DS - XS1
END DESCRIPTION:
XS GIS Cut Line= 4
       3055703.5      13924645.1      3055050.72      13924297.1
        3054974.      13924201.2      3054652.84      13924041.5
#Sta/Elev= 30
  4192.6  121.56  4402.6   120.9  4462.6  119.98  4482.6  120.34  4502.6  120.15
  4532.6  118.76  4572.6  118.87  4642.6  117.27  4702.6  116.82  4742.6   117.6
  4772.6  116.72  4852.6  116.28  4872.6  117.61  4882.6  116.56  4892.6  116.23
  4932.3  116.71 4953.21  115.66 4971.98  114.77 4994.51  107.49 4996.87  105.74
 5000.27  105.59  5004.3  105.89 5005.78  106.75 5021.12  110.43 5030.18  113.87
  5032.3  116.25  5065.1  115.59  5275.1   120.7  5295.1  121.72  5413.8  123.98
#Mann= 4 ,-1 , 0
  4192.6     .08       0  4872.6     .05       0 4953.21     .04       0
  5065.1      .1       0
#XS Ineff= 2 , 0
       0    4809  120.77    5199       0  122.47
Permanent Ineff=
       F       F
Bank Sta=4971.98,5032.3
XS Rating Curve= 0
Exp/Cntr=.3,.1

Type RM Length L Ch R = 1 ,2356.9  ,1225,1247.2,1317
BEGIN DESCRIPTION:
Cross Section K140-00-00-X1
END DESCRIPTION:
XS GIS Cut Line= 4
  3055764.657046 13924499.179377      3055461.27     13924340.98
      3055122.13     13923975.97 3054815.308010613923904.8030475
#Sta/Elev= 28
  4329.4   121.9  4369.4   121.3  4539.4   119.9  4569.4   119.2  4659.4   118.9
  4671.6   118.2  4691.6   117.2  4701.6   117.6  4861.6     116    4876  115.05
  4945.2  115.11    4971  115.55  4985.8   112.2    4996  106.29  4997.3  105.71
  4999.2  105.67  5002.7  105.66  5003.9  106.38  5008.5  110.98  5018.3  111.22
  5036.7   116.6  5044.8  116.76  5104.3  116.81  5169.8   116.6  5269.8   116.7
  5329.8   119.2  5409.8   118.2  5484.8  119.35
#Mann= 4 ,-1 , 0
  4329.4     .14       0  4945.2    .045       0    4971     .04       0
  5036.7     .14       0
Bank Sta=4971,5036.7
XS Rating Curve= 0
Exp/Cntr=.3,.1

Type RM Length L Ch R = 1 ,1109.7  ,28,41.1,35
BEGIN DESCRIPTION:
Cross Section K140-00-00-X1A
detention pond on right overbank ineffective below elev. 112
END DESCRIPTION:
XS GIS Cut Line= 4
      3056129.57      13923811.5      3056073.73     13923422.85
      3056158.49      13923212.4      3056140.04      13923045.8
#Sta/Elev= 30
    4460  119.85    4590   116.7    4630   116.3    4730   112.8    4790   112.7
    4840   113.5  4852.7   114.1  4884.5  117.11  4894.3  117.19  4923.1  110.41
  4967.4  106.54  4982.1  104.82  4983.7  104.29    4984  103.74  5016.3  103.82
  5017.1  104.94  5019.4  106.56    5022  110.12  5029.9  111.91  5047.9  117.43
  5078.9  117.54  5089.6   115.1  5109.6     113  5119.6   111.1  5129.6   109.9
  5139.6   110.4  5169.6   113.3  5179.6   115.3  5189.6     116  5247.1  116.23
#Mann= 5 ,-1 , 0
    4460     .14       0  4894.3    .055       0  5047.9     .14       0
  5089.6    .026       0  5189.6     .14       0
#Block Obstruct= 2 , 0
       0                    5079       0     112
Bank Sta=4894.3,5047.9
XS Rating Curve= 0
Exp/Cntr=.3,.1

Type RM Length L Ch R = 1 ,1068.6  ,0,0,0
BEGIN DESCRIPTION:
Cross Section K140-00-00-X1B
detention pond on right overbank ineffective below elev. 112
END DESCRIPTION:
XS GIS Cut Line= 4
 3056170.801527513923820.4677791      3056111.79     13923404.19
      3056190.86     13923230.99      3056173.36      13923051.8
#Sta/Elev= 30
  4487.1   119.4  4717.1   114.8  4767.1   112.2  4787.1   112.1  4827.1   113.2
  4857.1   112.7  4887.1   114.2    4906  116.79  4918.1  117.11    4933  113.53
  4973.4  113.16  4989.4  106.05  4998.6  103.18  5000.1  103.47  5001.5   104.9
  5003.7  104.57    5013  108.25  5021.2  113.12  5047.6  114.28  5064.7  117.25
  5081.3  118.03  5095.1  117.47  5097.9   118.2  5107.9   115.3  5127.9   110.7
  5137.9   109.4  5207.9   109.2  5227.9   110.1  5257.9   114.3  5277.9   116.2
#Mann= 5 ,-1 , 0
  4487.1     .14       0  4973.4    .055       0  5021.2     .14       0
  5107.9    .026       0  5207.9     .14       0
#Block Obstruct= 2 , 0
       0                    5097       0     112
Bank Sta=4973.4,5021.2
XS Rating Curve= 0
Exp/Cntr=.3,.1

Chan Stop Cuts=-1